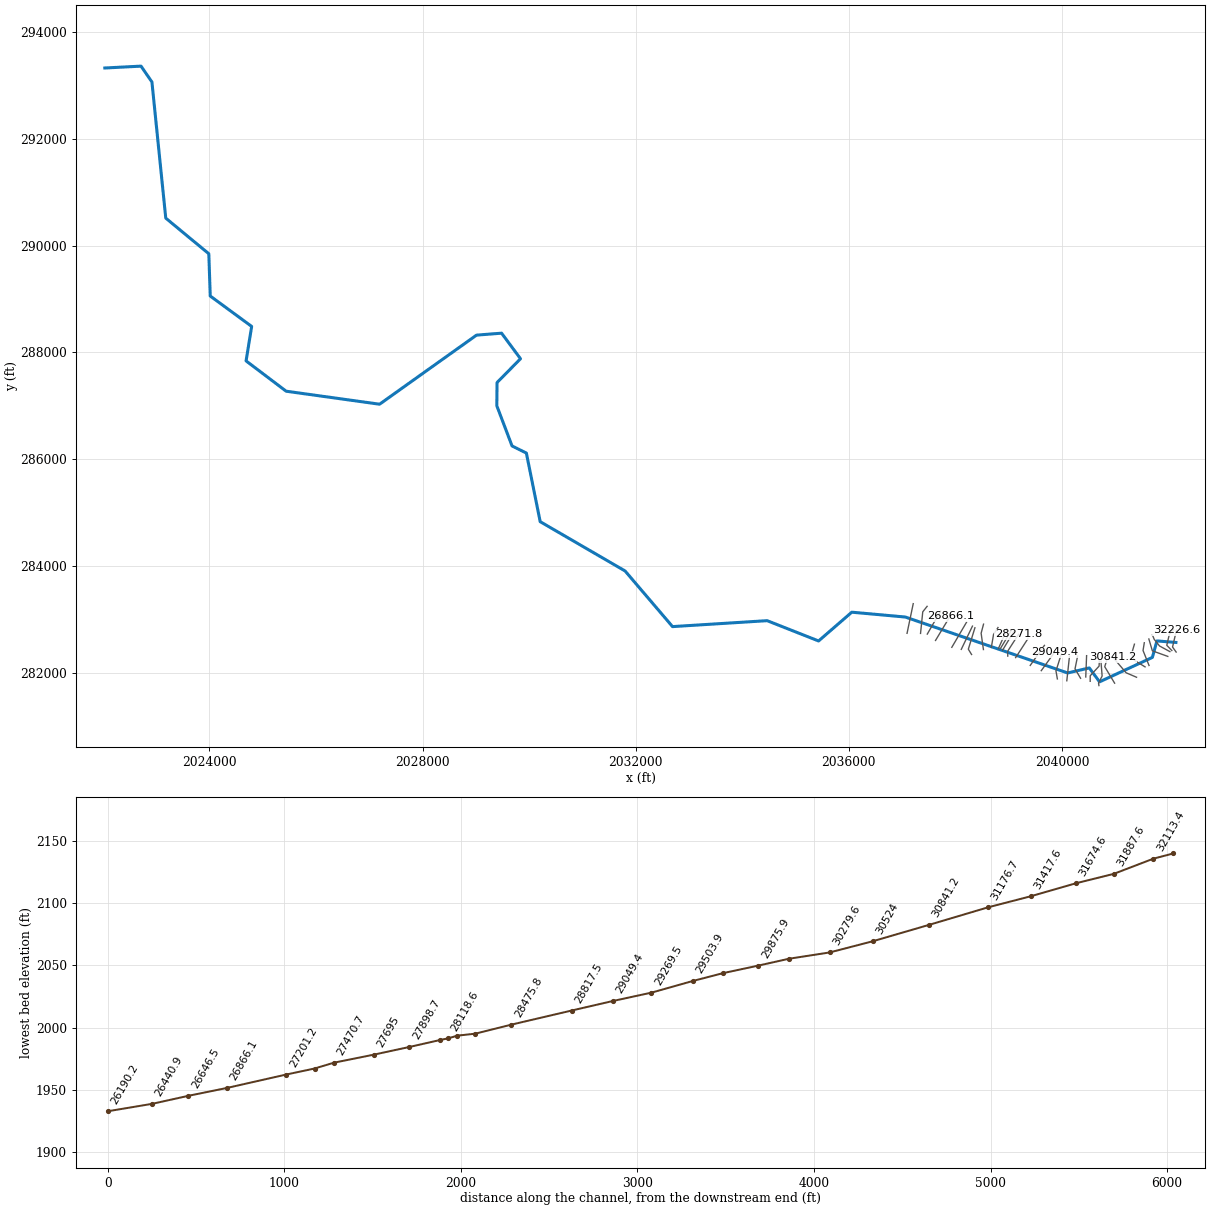
--- LICKCK1.prj (project) ---

Proj Title=LICKCK1
Current Plan=p01
Default Exp/Contr=0,0
English Units
Geom File=g01
Flow File=f01
Plan File=p01
BEGIN DESCRIPTION:
END DESCRIPTION:
DSS File=dss
DSS Export Rating Curves= 0
DSS Export Rating Curve Sorted= 0
DSS Export Volume Flow Curves= 0
DXF OffsetX= 0
DXF OffsetY= 0
DXF ScaleX= 0
DXF ScaleY= 0

--- LICKCK1.p01 (plan) ---

Plan Title=Floodplain
Program Version=4.10
Short Identifier=Floodplain
Geom File=g01
Flow File=f01
Subcritical Flow
K Sum by GR= 0
Std Step Tol= 0.01
Critical Tol= 0.01
Num of Std Step Trials= 20
Max Error Tol= 0.3
Flow Tol Ratio= 0.001
Split Flow NTrial= 30
Split Flow Tol= 0.02
Split Flow Ratio= 0.02
Log Output Level= 0
Friction Slope Method= 1
Unsteady Friction Slope Method= 2
Unsteady Bridges Friction Slope Method= 1
Parabolic Critical Depth
Global Vel Dist= 0 , 0 , 0
Global Log Level= 0
CheckData=True
Encroach Param=-1 ,0,0, 0
Run HTab= 0
Run UNet= 0
Run PostProcess= 0
Run WQNet= 0
UNET Theta= 0
UNET Theta Warmup= 0
UNET ZTol= 0
UNET ZSATol= 0
UNET MxIter= 0
UNET MaxInSteps= 0
UNET DtIC= 0
UNET DtMin= 0
UNET MaxCRTS= 0
UNET WFStab= 0
UNET SFStab= 0
UNET WFX= 1
UNET SFX= 1
UNET DSS MLevel= 1
UNET DZMax Abort= 0
UNET Convert EG Bridges= 0
UNET Use Existing IB Tables= 0
UNET Froude Reduction=False
UNET Froude Limit= 0
UNET Froude Power= 0
UNET Time Slicing=0,0, 5
UNET Junction Losses=0
DSS File=dss
Write IC File= 0
Write IC File at Sim End=0
Echo Input=False
Echo Parameters=False
Echo Output=False
Write Detailed= 0
WQ AD Non Conservative
WQ ULTIMATE=-1
WQ Max Comp Step=1HOUR
WQ Output Interval=15MIN
WQ Output Selected Increments= 0
WQ Output face flow=0
WQ Output face velocity=0
WQ Output face area=0
WQ Output face dispersion=0
WQ Output cell volume=0
WQ Output cell surface area=0
WQ Output cell continuity=0
WQ Output cumulative cell continuity=0
WQ Output face conc=0
WQ Output face dconc_dx=0
WQ Output face courant=0
WQ Output face peclet=0
WQ Output face adv mass=0
WQ Output face disp mass=0
WQ Output cell mass=0
WQ Output cell source sink temp=0
WQ Output cell source sink nsm=0
WQ Output MaxMinRange=-1
WQ Daily Max Min Mean=-1
WQ Daily Range=0
WQ Daily Time=0
WQ Create Restart=0
WQ Fixed Restart=0
WQ System Summary=0
WQ Use Fixed Temperature=0
Sorting and Armoring Iterations= 10
XS Update Threshold= 0.02
Hydraulics Update Threshold= 0.02
Energy Slope Method= 1
Volume Change Method= 0
XS Weighting Method= 0
Number of US Weighted Cross Sections= 1
Number of DS Weighted Cross Sections= 1
Upstream XS Weight=0.25
Main XS Weight=0.5
Downstream XS Weight=0.25
Number of DS XS's Weighted with US Boundary= 1
Upstream Boundary Weight= 1
Weight of XSs Associated with US Boundary= 0
Number of US XS's Weighted with DS Boundary= 1
Downstream Boundary Weight= 0.5
Weight of XSs Associated with DS Boundary= 0.5
Sediment Output Level= 4
Mass or Volume Output= 0
Output Increment Type= 1
Profile and TS Output Increment= 10
XS Output Flag= 0
XS Output Increment= 10
Disregard all LS=0
Disregard all Conn=0
Disregard all Breaches=0
Disregard all Pumps=0

--- LICKCK1.f01 (steady flow) ---

Flow Title=NFF Regression Equation
Program Version=4.00
Number of Profiles=1
Profile Names=P100yr
River Rch & RM=LICKCK1,Main      ,32226.6
464.3555
River Rch & RM=LICKCK1,Main      ,31887.6
594.3842
River Rch & RM=LICKCK1,Main      ,31176.7
607.2476
River Rch & RM=LICKCK1,Main      ,30524
754.6883
River Rch & RM=LICKCK1,Main      ,29269.5
772.2559
River Rch & RM=LICKCK1,Main      ,29049.4
915.2665
River Rch & RM=LICKCK1,Main      ,26866.1
979.8044
River Rch & RM=LICKCK1,Main      ,21212
1078.323
River Rch & RM=LICKCK1,Main      ,20965.6
1250.724
River Rch & RM=LICKCK1,Main      ,13613.5
1372.781
River Rch & RM=LICKCK1,Main      ,13195.4
2247.796
River Rch & RM=LICKCK1,Main      ,8557.9
2290.498
River Rch & RM=LICKCK1,Main      ,8265.8
2577.349
River Rch & RM=LICKCK1,Main      ,2665.4
2855.638
River Rch & RM=LICKCK1,Main      ,1184.2
3167.964
River Rch & RM=LICKCK1,Main      ,144.4
3189.027
Boundary for River Rch & Prof#=LICKCK1,Main      ,1
Up Type=0
Dn Type=3
Dn Slope=0.008312

--- LICKCK1.g01 (geometry) ---

Geom Title=USGS 10m DEM
Program Version=4.10

River Reach=LICKCK1         ,Main
Reach XY= 30
      2042138.05      282567.872     2041781.958      282596.088
      2041696.71       282287.69     2040705.562      281830.162
     2040512.641      282090.241     2040106.489      281996.301
     2037061.351       283043.64     2036055.926      283134.529
     2035432.295      282595.548     2034466.928      282975.943
     2032691.764      282864.368     2031801.048      283906.775
      2030208.29      284830.087     2029948.785      286115.075
     2029679.877      286248.588     2029394.046      287000.776
     2029398.434      287435.792     2029838.656      287881.893
     2029483.745      288361.179     2029013.076      288324.219
     2027193.844      287030.228     2025440.832      287273.908
     2024688.627      287841.598     2024793.662      288487.242
     2024016.318      289056.687     2023989.472      289848.523
     2023181.509      290515.888     2022921.874      293065.888
     2022717.013       293363.11     2022037.758      293328.188

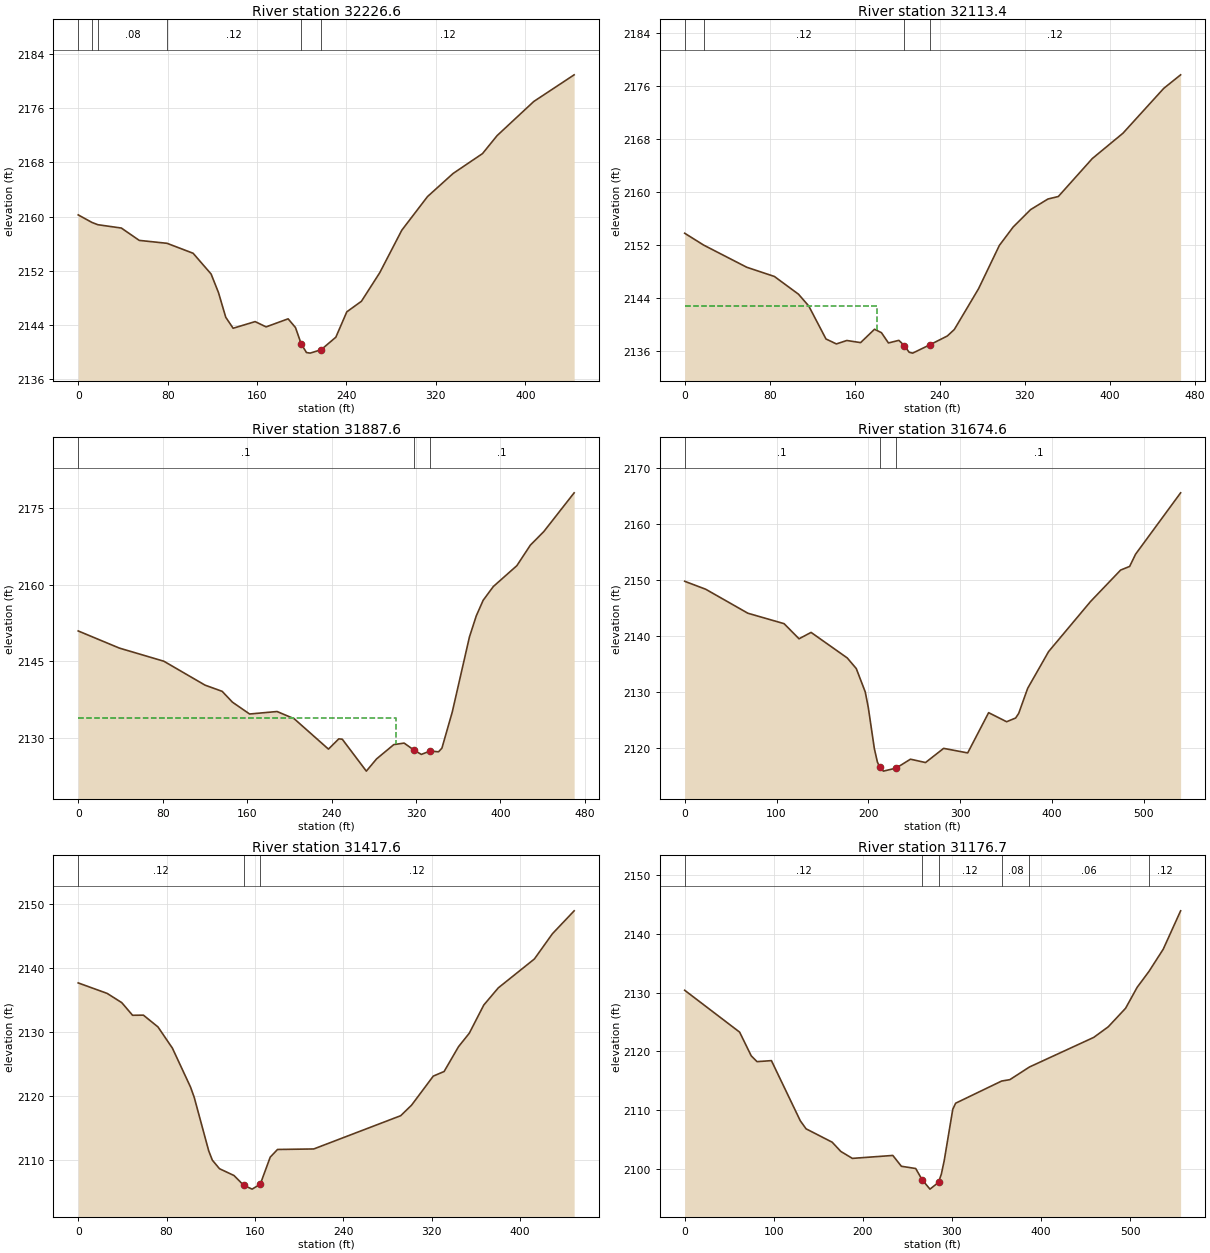
Type RM Length L Ch R = 1 ,32226.6 ,113.4,113.3,113.3
XS GIS Cut Line= 3
     2042142.733      282387.955     2042075.024      282481.705
     2042149.677       282801.15
#Sta/Elev= 30
       0 2160.27   12.222159.164   17.572158.822    38.6 2158.33    54.6 2156.51
   79.462156.079   102.8 2154.61   118.9 2151.55   125.5 2148.81     132 2145.17
   138.6 2143.55   158.3 2144.53   168.1 2143.75   187.8 2144.94   194.4 2143.65
   199.5 2141.24   204.2 2139.97   207.5 2139.88   217.3 2140.38   230.5 2142.23
   240.3 2145.97   253.4 2147.53   269.8 2151.75   289.5 2158.01   312.5 2162.97
   335.4 2166.38   361.7 2169.31   374.8 2171.97   407.6    2177   443.7 2180.93
#Mann= 6 ,-1 , 0
       0     .06       0   12.22     .12       0   17.57     .08       0
   79.46     .12       0   199.5    .045       0   217.3     .12       0
Bank Sta=199.5,217.3
XS Rating Curve= 0 ,0
Exp/Cntr=0.3,0.1

Type RM Length L Ch R = 1 ,32113.4 ,204.9,225.8,246.3
XS GIS Cut Line= 4
     2042061.844      282416.775     2041966.792      282514.431
     2042016.271      282724.067     2042094.396      282808.702
#Sta/Elev= 30
       0 2153.79   17.932151.992    58.4 2148.65    84.4 2147.26   107.1 2144.58
   116.8 2142.79     133 2137.81   142.8 2137.06   152.6 2137.58   165.6 2137.26
   178.7 2139.28   185.2 2138.76   191.8 2137.21   201.6  2137.6  206.68 2136.82
   211.3  2135.8   214.6 2135.67   230.9 2136.94   247.2 2138.26   253.8 2139.24
   276.6  2145.4   296.2 2151.95   309.2 2154.73   325.6 2157.36   341.9 2158.96
   351.7 2159.34   383.7 2165.08   412.5  2168.9   450.9 2175.68   466.8 2177.73
#Mann= 4 ,-1 , 0
       0     .06       0   17.93     .12       0  206.68    .045       0
   230.9     .12       0
#XS Ineff= 2 , 0
          181.11 2142.74
Permanent Ineff=
       F       F
Bank Sta=206.68,230.9
XS Rating Curve= 0 ,0
Exp/Cntr=0.3,0.1

Type RM Length L Ch R = 1 ,31887.6 ,200.1,213,224.3
XS GIS Cut Line= 4
     2042025.386      282395.942     2041831.375       282501.41
     2041731.274      282625.803     2041697.261      282708.442
#Sta/Elev= 30
       0 2150.91      39 2147.55    81.2 2144.97   120.2 2140.28   136.4 2139.07
   146.1 2136.95   162.4 2134.62   188.4 2135.11   204.6  2133.7   237.1 2127.74
   246.9 2129.75   250.2 2129.68     273 2123.42   282.7 2125.82     299 2128.62
   308.8 2128.92   318.4 2127.51   325.1  2126.7   333.4 2127.36   341.4 2127.21
   344.6 2127.92   354.4    2135   370.7 2149.74   377.2 2153.89   383.7 2156.93
   393.3 2159.62   415.6 2163.71   428.4 2167.74   441.1 2170.39   469.9    2178
#Mann= 3 , 0 , 0
       0      .1       0   318.4    .045       0   333.4      .1       0
#XS Ineff= 2 , 0
          301.14 2133.83
Permanent Ineff=
       F       F
Bank Sta=318.4,333.4
XS Rating Curve= 0 ,0
Exp/Cntr=0.3,0.1

Type RM Length L Ch R = 1 ,31674.6 ,274.5,257,237.9
XS GIS Cut Line= 3
     2041986.483      282306.358     2041696.552      282410.525
      2041630.58      282632.747
#Sta/Elev= 30
       0  2149.8    22.9 2148.38    68.8  2144.1   108.2 2142.24   124.5 2139.54
   137.6 2140.68     177 2136.12   186.8 2134.23   196.6 2130.05   199.9 2127.27
   206.5 2119.94   209.8 2117.56  212.22 2116.65   216.3 2115.93   230.2 2116.47
   245.8 2118.06   262.2 2117.46   281.9 2119.99   308.1 2119.18   330.9 2126.36
   350.5 2124.74   360.3 2125.41   363.6 2126.22   373.4  2130.7   396.2 2137.26
   441.9  2146.2   474.6  2151.8   484.4 2152.45   490.9 2154.64   539.9 2165.58
#Mann= 3 , 0 , 0
       0      .1       0  212.22    .045       0   230.2      .1       0
Bank Sta=212.22,230.2
XS Rating Curve= 0 ,0
Exp/Cntr=0.3,0.1

Type RM Length L Ch R = 1 ,31417.6 ,239.6,240.9,240.8
XS GIS Cut Line= 3
     2041633.618      282136.653      2041521.48      282416.775
     2041545.076      282562.001
#Sta/Elev= 30
       0  2137.7    26.2 2136.06    39.4 2134.62    49.2 2132.64      59 2132.66
    72.2 2130.82    85.3 2127.49   101.7  2121.4     105 2119.81   118.1 2111.46
   121.4 2109.99   127.9 2108.65     141 2107.59   149.8 2106.06   157.4 2105.46
   164.8 2106.23   173.8 2110.46   180.4 2111.66   213.2 2111.74   291.9 2116.94
   301.7 2118.58   321.4 2123.13   331.2 2123.85   344.2 2127.72     354 2129.84
   367.1 2134.24   380.2 2136.92   412.9 2141.44   429.2 2145.38   448.9 2148.97
#Mann= 3 ,-1 , 0
       0     .12       0   149.8    .045       0   164.8     .12       0
Bank Sta=149.8,164.8
XS Rating Curve= 0 ,0
Exp/Cntr=0.3,0.1

Type RM Length L Ch R = 1 ,31176.7 ,328.7,335.5,340.7
XS GIS Cut Line= 4
     2041559.399      282110.178     2041359.746      282231.705
     2041305.927      282351.497     2041359.746      282535.525
#Sta/Elev= 30
       0 2130.39    61.7 2123.28    74.7 2119.26    81.2 2118.27    97.4 2118.44
   129.8 2108.23   136.3 2106.86   165.6 2104.59   175.3 2103.02   188.3 2101.84
   233.7 2102.34   243.3  2100.5   259.4 2100.12   266.6 2098.21   275.4 2096.62
     285 2097.77   288.2 2099.19   291.4 2101.47     301 2110.18   304.2 2111.21
  355.852114.974   365.1 2115.21  387.08 2117.36   459.3 2122.39   475.6 2124.19
     495 2127.33     508 2130.89  521.312133.602   537.3 2137.37   556.8 2143.88
#Mann= 6 ,-1 , 0
       0     .12       0   266.6    .045       0     285     .12       0
  355.85     .08       0  387.08     .06       0  521.31     .12       0
Bank Sta=266.6,285
XS Rating Curve= 0 ,0
Exp/Cntr=0.3,0.1

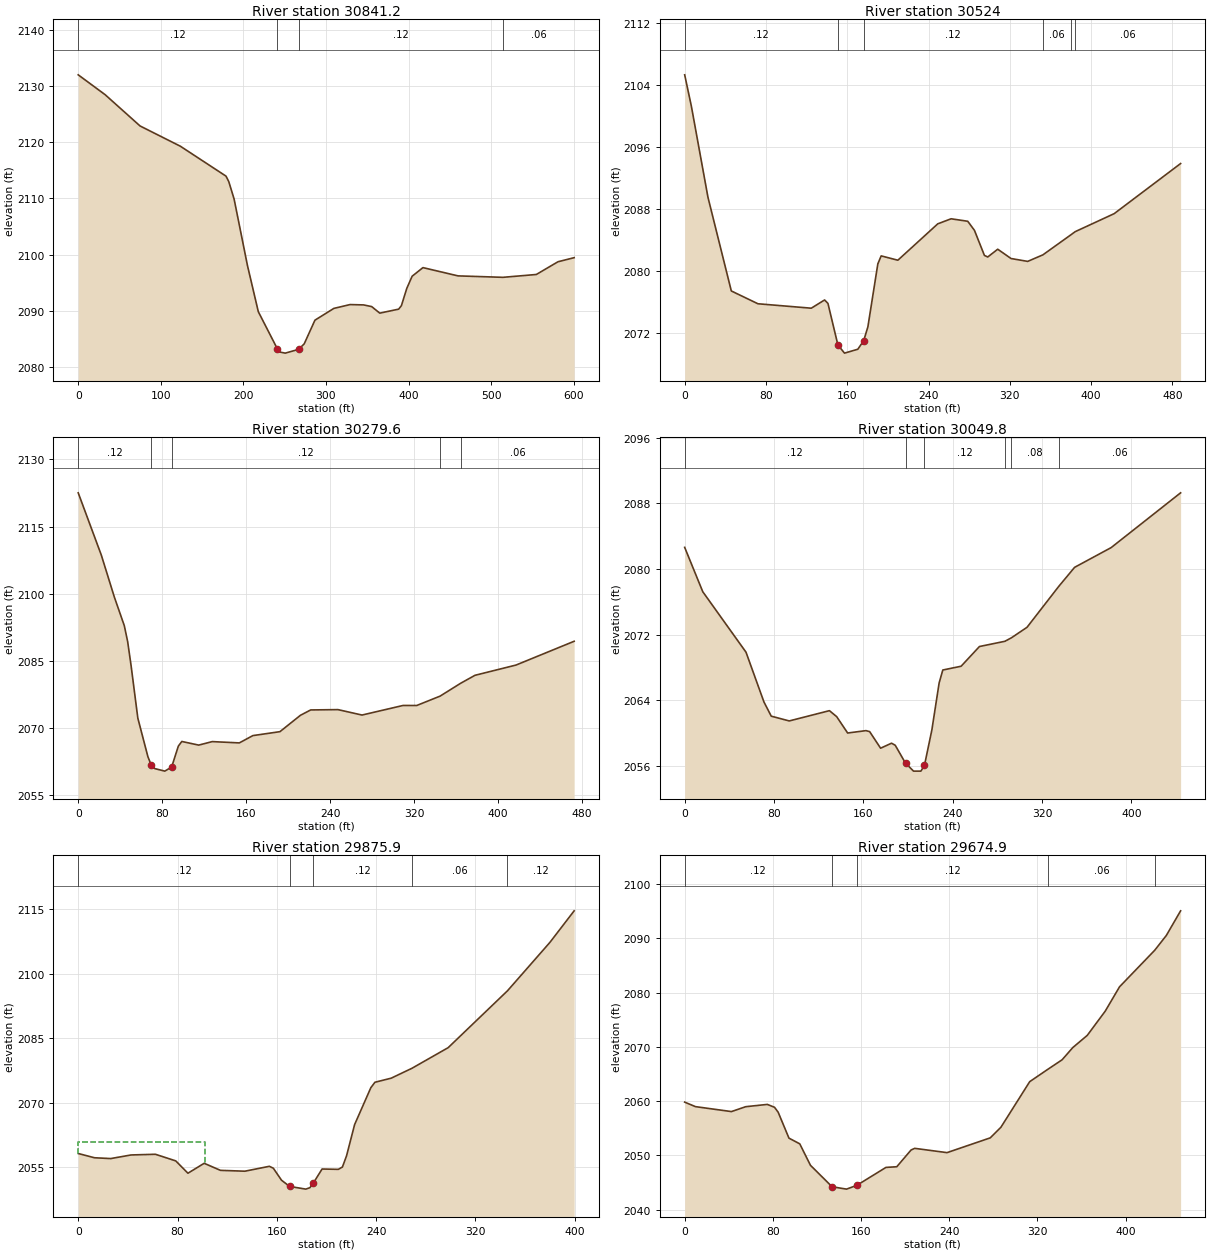
Type RM Length L Ch R = 1 ,30841.2 ,319.9,317.1,312.2
XS GIS Cut Line= 3
     2041399.677      281915.733     2041205.233      281999.067
      2040951.76      282294.205
#Sta/Elev= 30
       0 2131.97    32.6 2128.44    74.9 2122.88   123.7 2119.28     179 2113.96
   182.3    2113   188.8 2109.89     205 2098.05   218.1 2089.87     241 2083.31
   244.2 2082.69   250.8  2082.5   267.1 2083.18   273.7 2084.15   286.7 2088.36
   309.6 2090.45   329.2 2091.13   345.6 2091.07   355.4 2090.77   365.2 2089.61
   388.1 2090.32   391.4 2090.94   397.9    2094   404.4 2096.17   417.5  2097.7
     460 2096.23  514.422095.974   554.8 2096.48     581 2098.74   600.6 2099.47
#Mann= 4 ,-1 , 0
       0     .12       0     241    .045       0   267.1     .12       0
  514.42     .06       0
Bank Sta=241,267.1
XS Rating Curve= 0 ,0
Exp/Cntr=0.3,0.1

Type RM Length L Ch R = 1 ,30524   ,266.6,244.4,221
XS GIS Cut Line= 3
     2040988.219      281804.622     2040802.455       282113.65
     2040841.141      282235.134
#Sta/Elev= 30
       0 2105.28     6.6 2101.23    22.9 2089.51    45.9 2077.43    72.1 2075.78
   124.6 2075.21   137.7 2076.27     141 2075.83   150.8 2070.47   157.3 2069.42
   170.4 2069.92   176.2 2071.03   180.3  2072.8   190.1 2080.92   193.4 2081.95
   209.8 2081.39   249.1 2086.08   262.2 2086.73   278.6 2086.41   285.2 2085.24
     295 2082.01   298.3 2081.81   308.1 2082.81   321.2 2081.61   337.6 2081.24
  352.562082.083  380.622084.714  384.362085.071   422.7 2087.39   488.1 2093.85
#Mann= 6 ,-1 , 0
       0     .12       0   150.8    .045       0   176.2     .12       0
  352.56     .06       0  380.62     .08       0  384.36     .06       0
Bank Sta=150.8,176.2
XS Rating Curve= 0 ,0
Exp/Cntr=0.3,0.1

Type RM Length L Ch R = 1 ,30279.6 ,235,229.8,223.8
XS GIS Cut Line= 4
     2040693.572      281759.874     2040686.135      281806.358
     2040753.844      281938.303     2040731.549      282214.518
#Sta/Elev= 30
       0 2122.55      22 2108.66    34.5 2099.23    43.9  2092.9    47.1 2089.35
    50.3 2084.11    56.8 2072.25    66.4 2063.64    69.6 2061.76    72.9 2060.99
    82.5 2060.42      89 2061.32    95.4    2066    98.7 2067.04   114.8 2066.23
   127.7 2067.01   153.5 2066.72   166.4 2068.35   192.2 2069.23   211.7 2072.88
   221.5 2074.08   247.5 2074.15   270.4 2072.94   309.5 2075.08   322.5 2075.07
  344.772077.162  364.412080.039     378 2081.81   417.1  2084.1   472.5 2089.41
#Mann= 5 ,-1 , 0
       0     .12       0    69.6    .045       0      89     .12       0
  344.77     .08       0  364.41     .06       0
Bank Sta=69.6,89
XS Rating Curve= 0 ,0
Exp/Cntr=0.3,0.1

Type RM Length L Ch R = 1 ,30049.8 ,157.6,173.9,189.7
XS GIS Cut Line= 4
     2040529.726      281840.169     2040529.885      281943.511
     2040696.552      282124.067     2040701.167      282218.858
#Sta/Elev= 30
       0 2082.63    16.2 2077.23    54.9 2069.87      71  2063.8    77.5 2062.08
    93.6  2061.5   129.6 2062.75   136.1 2062.02   145.9 2060.03   162.3 2060.32
   165.6  2060.2   175.4 2058.18   185.2 2058.79   188.5 2058.54   197.7 2056.36
   204.9 2055.39   211.5 2055.39   214.7 2056.11   221.3  2060.4   227.8 2066.12
   231.1  2067.7   247.5 2068.16   263.9 2070.56  286.662071.195  292.552071.623
   306.5  2072.9  334.872077.875   349.1  2080.2   381.8  2082.6     444 2089.27
#Mann= 6 ,-1 , 0
       0     .12       0   197.7    .045       0   214.7     .12       0
  286.66     .06       0  292.55     .08       0  334.87     .06       0
Bank Sta=197.7,214.7
XS Rating Curve= 0 ,0
Exp/Cntr=0.3,0.1

Type RM Length L Ch R = 1 ,29875.9 ,187.7,201,213.7
XS GIS Cut Line= 2
     2040446.552      281920.942     2040462.177      282320.247
#Sta/Elev= 30
       0 2058.17    13.1 2057.18    26.2 2056.99    42.6 2057.83    62.2 2057.99
    78.6 2056.45    88.4 2053.58   101.5 2055.89   114.6 2054.25   134.3 2054.05
     154 2055.19   157.2 2054.75   163.8 2051.96   170.3 2050.51   183.4 2049.88
   186.7 2050.22   189.4 2051.27   196.5 2054.56   209.6 2054.48   212.9 2055.03
   216.2 2057.62   222.7 2064.89   235.8 2073.49   239.1 2074.75   252.2  2075.7
  268.972078.008   298.1  2082.8  345.872096.027     380 2107.27   399.6 2114.64
#Mann= 5 ,-1 , 0
       0     .12       0   170.3    .045       0   189.4     .12       0
  268.97     .06       0  345.87     .12       0
#XS Ineff= 2 , 0
          102.27 2060.79
Permanent Ineff=
       F       F
Bank Sta=170.3,189.4
XS Rating Curve= 0 ,0
Exp/Cntr=0.3,0.1

Type RM Length L Ch R = 1 ,29674.9 ,185.5,170.9,156.2
XS GIS Cut Line= 3
      2040349.33      281896.636     2040245.163      282073.719
     2040293.774      282313.303
#Sta/Elev= 30
       0 2059.82     9.8 2058.99    42.4 2058.08    55.4 2058.98      75  2059.4
    81.5 2058.87    84.8 2057.97    94.6 2053.19   104.4 2052.14   114.1 2048.19
   133.7 2044.24   146.8  2043.8   156.1 2044.49   182.6  2047.8   192.4 2047.92
   205.4 2051.01   208.7 2051.31     238 2050.52   277.2 2053.24   286.9  2055.2
     313 2063.59   329.62065.885   342.4 2067.62   352.1 2069.87   365.2 2072.11
   381.5 2076.57   394.5 2081.06  426.412087.789   436.9  2090.5   449.9 2095.05
#Mann= 5 ,-1 , 0
       0     .12       0   133.7    .045       0   156.1     .12       0
   329.6     .06       0  426.41     .12       0
Bank Sta=133.7,156.1
XS Rating Curve= 0 ,0
Exp/Cntr=0.3,0.1

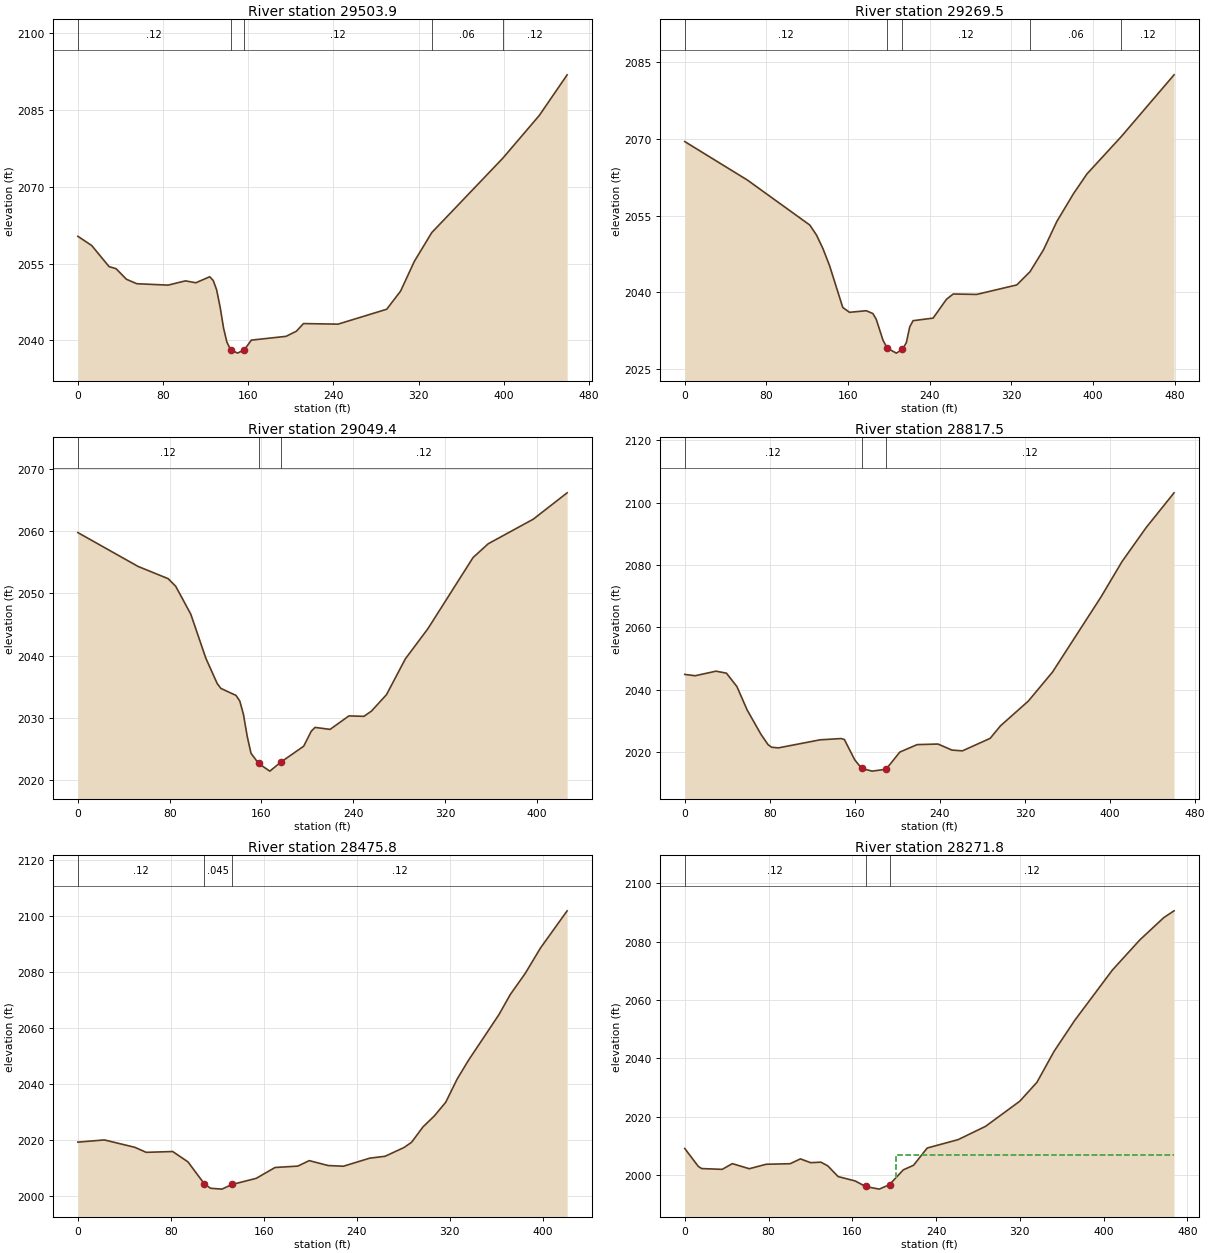
Type RM Length L Ch R = 1 ,29503.9 ,238.4,234.4,229.6
XS GIS Cut Line= 2
     2040090.649      281849.761     2040140.996      282306.358
#Sta/Elev= 30
       0 2060.32      13 2058.52    29.3  2054.4    35.8 2054.01    45.6 2051.93
    55.4 2051.06    84.7 2050.79     101 2051.62   110.8 2051.25   123.8 2052.42
   127.1 2051.69   130.3 2049.86   133.6 2046.47   136.8  2042.4   139.9 2039.67
   143.4 2038.19   149.9 2037.51   156.4 2038.19   162.9 2040.05   195.5 2040.79
   205.2 2041.79   211.8 2043.28   244.3 2043.17     290 2046.08     303 2049.62
     316 2055.45  332.262061.039  399.032075.578   433.3 2083.93   459.4 2091.85
#Mann= 5 ,-1 , 0
       0     .12       0   143.4    .045       0   156.4     .12       0
  332.26     .06       0  399.03     .12       0
Bank Sta=143.4,156.4
XS Rating Curve= 0 ,0
Exp/Cntr=0.3,0.1

Type RM Length L Ch R = 1 ,29269.5 ,227.2,220.1,213.1
XS GIS Cut Line= 3
     2039913.566      281884.483     2039887.524      282033.789
     2039986.483      282346.289
#Sta/Elev= 30
       0 2069.42    61.3 2061.92   122.5 2053.14     129 2051.21   135.4 2048.54
   141.9  2045.2   154.8 2037.07   161.4 2036.12   177.8 2036.43   184.3 2035.88
   187.6 2034.76   194.2 2030.69   198.3 2029.14   207.3 2028.16   213.3  2028.9
   217.1 2030.21   220.4 2033.27   223.7 2034.49   243.3 2034.99   256.4 2038.66
     263 2039.69     286 2039.61   325.3 2041.46  338.282044.043   351.5 2048.32
   364.6 2053.86     381  2059.3   394.1 2063.12  427.872070.436   479.4 2082.44
#Mann= 5 ,-1 , 0
       0     .12       0   198.3    .045       0   213.3     .12       0
  338.28     .06       0  427.87     .12       0
Bank Sta=198.3,213.3
XS Rating Curve= 0 ,0
Exp/Cntr=0.3,0.1

Type RM Length L Ch R = 1 ,29049.4 ,231.5,231.9,232
XS GIS Cut Line= 2
     2039611.483      282038.997     2039861.483      282384.483
#Sta/Elev= 30
       0  2059.8    52.5 2054.35    78.7 2052.38    85.3 2051.15    98.4 2046.67
   111.5 2039.59   121.4 2035.51   124.6 2034.72   137.8 2033.59   141.1 2032.69
   144.3 2030.54   147.6 2026.99   150.9 2024.27   157.5 2022.63   167.3  2021.4
   177.1 2022.88   196.8 2025.41   203.4 2027.83   206.7 2028.44   219.8 2028.12
   236.2 2030.29   249.3 2030.22   255.9 2031.07     269 2033.72   285.4 2039.47
   305.1 2044.34   344.4 2055.78   357.6    2058   396.9 2061.96   426.4  2066.2
#Mann= 3 ,-1 , 0
       0     .12       0   157.5    .045       0   177.1     .12       0
Bank Sta=157.5,177.1
XS Rating Curve= 0 ,0
Exp/Cntr=0.3,0.1

Type RM Length L Ch R = 1 ,28817.5 ,340.3,341.7,342.8
XS GIS Cut Line= 2
     2039404.509      282137.478      2039670.51      282512.955
#Sta/Elev= 30
       0 2044.86     9.8 2044.44    29.4 2045.91    39.2 2045.26      49 2040.98
    58.7 2033.42    71.8 2025.54    78.3 2022.32    81.6 2021.48    88.1 2021.27
   127.3 2023.86   146.9 2024.26   150.1 2023.96   159.9 2017.41   166.4 2014.67
   176.2  2013.8   189.3  2014.4   202.3 2019.93   218.6 2022.32   238.2  2022.5
   251.3 2020.56   261.1 2020.31   287.2 2024.32     297 2028.37   323.1 2036.29
   345.9 2045.63   391.6  2069.8   411.2 2081.08     434 2092.05   460.2 2103.19
#Mann= 3 ,-1 , 0
       0     .12       0   166.4    .045       0   189.3     .12       0
Bank Sta=166.4,189.3
XS Rating Curve= 0 ,0
Exp/Cntr=0.3,0.1

Type RM Length L Ch R = 1 ,28475.8 ,205.4,204,201.9
XS GIS Cut Line= 2
     2039131.072      282283.962     2039360.397      282637.087
#Sta/Elev= 30
       0 2019.24    22.8 2020.04      49  2017.4    58.8 2015.61    81.6  2015.9
    94.7 2012.23  108.87 2004.35   114.2 2002.79     124 2002.48  132.65 2004.14
   153.4 2006.31   169.7  2010.2   189.3  2010.7   199.1 2012.65   215.4  2010.9
   228.5 2010.65   251.3 2013.54   264.4  2014.2   280.7 2017.33   287.2 2019.19
     297 2024.67   306.8  2028.6   316.6 2033.47   326.4 2041.73   336.2 2048.47
   362.3 2064.68   372.1 2071.88   385.2 2079.57   398.2 2088.55   421.1 2101.79
#Mann= 3 ,-1 , 0
       0     .12       0  108.87    .045       0  132.65     .12       0
Bank Sta=108.87,132.65
XS Rating Curve= 0 ,0
Exp/Cntr=0.3,0.1

Type RM Length L Ch R = 1 ,28271.8 ,99.4,101.6,103.5
XS GIS Cut Line= 3
     2038982.634      282312.174      2038983.01      282406.185
     2039184.399      282720.421
#Sta/Elev= 30
       0 2009.14      13 2002.99    16.2 2002.28    35.7 2002.01    45.4 2003.97
    61.6 2002.23    77.8 2003.76   100.6 2003.94   110.4  2005.6   120.2  2004.3
     130 2004.47   136.6  2003.2   146.4 1999.54   162.8 1998.03   172.6 1996.15
   185.7 1995.24   195.5 1996.78   208.6 2001.83   218.4  2003.4   231.5 2009.32
     261 2012.19   287.2 2016.74   319.9 2025.35   336.3 2031.84   352.6 2042.41
   372.3 2053.01   408.3 2070.26   434.5 2080.58   457.4 2088.23   467.2 2090.55
#Mann= 3 ,-1 , 0
       0     .12       0   172.6    .045       0   195.5     .12       0
#XS Ineff= 2 , 0
                           201.7         2007.06
Permanent Ineff=
       F       F
Bank Sta=172.6,195.5
XS Rating Curve= 0 ,0
Exp/Cntr=0.3,0.1

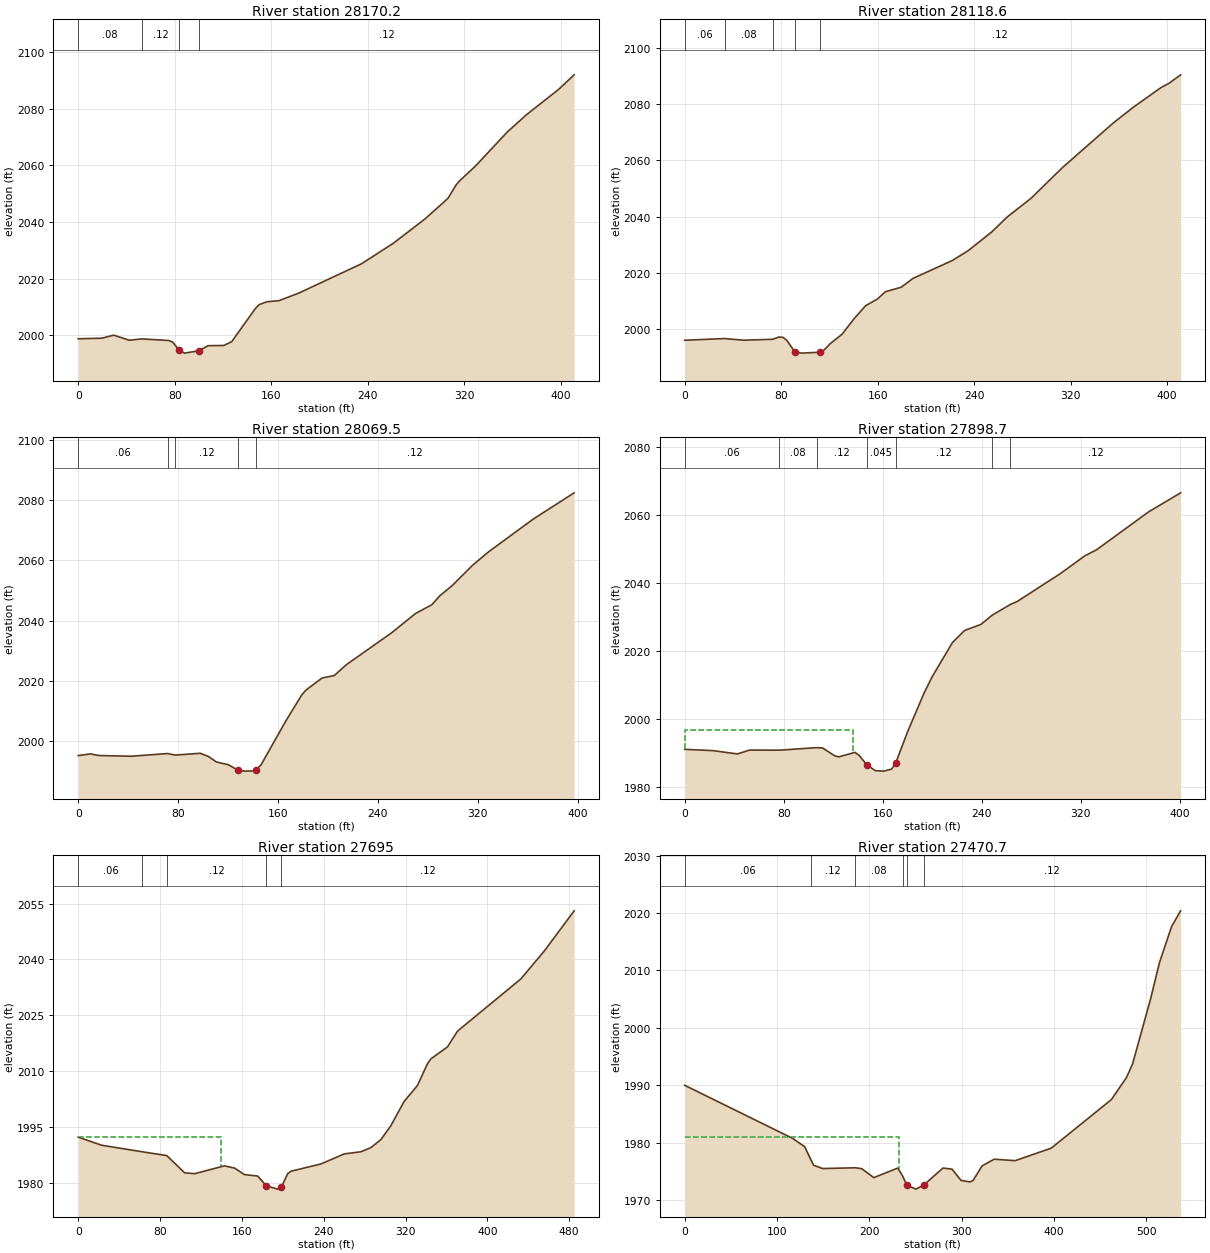
Type RM Length L Ch R = 1 ,28170.2 ,51.7,51.6,51.8
XS GIS Cut Line= 2
     2038886.656      282424.414     2039098.462      282776.844
#Sta/Elev= 30
       0 1998.71    19.6 1998.93    29.4    2000    42.4 1998.21   52.851998.672
    75.1 1998.11    78.3 1997.56   83.67 1994.69    88.1 1993.65   100.1 1994.49
   107.7 1996.28   120.7 1996.35   127.3 1997.71   146.8 2009.36   150.1  2010.8
   156.6 2011.81   166.4 2012.17   182.8 2014.84     235 2025.24   261.1 2032.41
   287.2 2040.94   303.5 2047.13   306.8 2048.47   313.3 2053.06   316.5  2054.6
   329.6 2059.83   355.7 2071.74     372 2077.98   398.1 2086.73   411.2 2091.96
#Mann= 4 ,-1 , 0
       0     .08       0   52.85     .12       0   83.67    .045       0
   100.1     .12       0
Bank Sta=83.67,100.1
XS Rating Curve= 0 ,0
Exp/Cntr=0.3,0.1

Type RM Length L Ch R = 1 ,28118.6 ,45.7,49.1,51.6
XS GIS Cut Line= 2
     2038841.517      282447.851     2039053.323      282800.282
#Sta/Elev= 30
       0 1996.08   33.14 1996.69      49  1996.1   72.821996.425    78.3 1997.23
    81.6 1997.09    84.8    1996    91.4  1991.9    96.8 1991.51   111.8 1991.82
   114.2 1992.02   120.7 1994.88   130.5 1998.24   140.3 2003.66   150.1 2008.38
   159.9 2010.75   166.4 2013.33   179.5 2014.92   189.3 2018.06   221.9 2024.41
     235 2027.89   254.5 2034.53   267.6 2039.94   287.2 2046.52   313.3 2057.46
   355.7  2073.4     372 2078.87   394.9 2085.84   401.4 2087.32   411.2 2090.38
#Mann= 5 ,-1 , 0
       0     .06       0   33.14     .08       0   72.82     .12       0
    91.4    .045       0   111.8     .12       0
Bank Sta=91.4,111.8
XS Rating Curve= 0 ,0
Exp/Cntr=0.3,0.1

Type RM Length L Ch R = 1 ,28069.5 ,165.6,170.8,176.4
XS GIS Cut Line= 2
     2038805.059      282447.851     2038966.517      282810.698
#Sta/Elev= 30
       0 1995.22     9.8  1995.8    16.3 1995.26    42.3 1995.01   71.561995.911
   77.681995.399    97.7 1995.99   104.2 1994.96   110.7 1993.11   120.4 1992.18
   127.7 1990.41   133.5 1990.07     140 1990.14   142.7  1990.6   146.5  1992.2
     166 2006.52     179 2015.34   182.3 2016.94   195.3 2020.99   205.1  2021.8
   214.8 2025.42   250.7  2035.9   270.2 2042.41   283.2  2045.3   289.7 2048.32
   299.5 2051.66   315.8 2058.39   328.8 2062.92   364.6 2073.79   397.2 2082.46
#Mann= 5 ,-1 , 0
       0     .06       0   71.56     .08       0   77.68     .12       0
   127.7    .045       0   142.7     .12       0
Bank Sta=127.7,142.7
XS Rating Curve= 0 ,0
Exp/Cntr=0.3,0.1

Type RM Length L Ch R = 1 ,27898.7 ,196.3,203.6,210.2
XS GIS Cut Line= 3
     2038674.404      282474.334     2038715.784      282716.601
     2038799.474      282846.896
#Sta/Elev= 30
       0    1991    22.9 1990.62    42.6 1989.65    52.4 1990.78   76.561990.756
  106.53  1991.5   111.4 1991.41   121.2 1989.09   124.5 1988.79   137.6  1990.1
   140.9 1989.23     147  1986.5     154 1984.72   160.6 1984.58   167.1 1985.16
   170.4 1986.91   180.2 1996.31   193.3 2007.53   199.9 2012.39   216.3 2022.48
   226.1 2026.04   239.2  2027.8  248.542030.576  262.972033.684   268.4 2034.53
   303.8 2042.88   323.2 2048.02   332.9 2049.87   374.8    2061   400.6  2066.6
#Mann= 7 ,-1 , 0
       0     .06       0   76.56     .08       0  106.53     .12       0
     147    .045       0   170.4     .12       0  248.54     .08       0
  262.97     .12       0
#XS Ineff= 2 , 0
          136.36 1996.82
Permanent Ineff=
       F       F
Bank Sta=147,170.4
XS Rating Curve= 0 ,0
Exp/Cntr=0.3,0.1

Type RM Length L Ch R = 1 ,27695   ,235.1,224.3,213.8
XS GIS Cut Line= 3
     2038526.037       282434.57      2038483.01      282740.386
     2038528.149      282910.525
#Sta/Elev= 30
       0 1992.32    22.8 1990.14    62.81988.369   86.531987.359     104 1982.74
   113.8 1982.49     143  1984.6   152.8    1984   162.5 1982.25   175.5 1981.86
   183.7 1979.27     195 1978.35   198.7 1978.96   204.8 1982.51     208 1983.16
   237.3 1985.11   260.1 1987.81   276.3 1988.38   286.1 1989.49   295.8 1991.63
   305.6 1995.36   318.6 2001.89   331.6 2006.16   341.4 2012.01   344.7 2013.31
     361 2016.54   370.8 2020.77   432.7 2034.78   455.5 2042.24   484.8 2053.06
#Mann= 5 ,-1 , 0
       0     .06       0    62.8     .08       0   86.53     .12       0
   183.7    .045       0   198.7     .12       0
#XS Ineff= 2 , 0
           139.2 1992.36
Permanent Ineff=
       F       F
Bank Sta=183.7,198.7
XS Rating Curve= 0 ,0
Exp/Cntr=0.3,0.1

Type RM Length L Ch R = 1 ,27470.7 ,112,109.8,106.5
XS GIS Cut Line= 3
     2038303.598      282341.869     2038242.834      282441.695
     2038366.532      282843.171
#Sta/Elev= 30
       0 1990.02   116.9 1980.78   129.9 1979.34  137.251976.872   139.7  1976.1
   149.4 1975.53  184.751975.666   191.8  1975.5   204.8 1973.95   230.8 1975.62
  235.87 1974.27   240.6 1972.64   250.4 1971.95   258.7 1972.64   279.7 1975.62
   289.5 1975.43   299.2 1973.47     309  1973.2   312.3 1973.46     322 1975.99
   335.1 1977.16   357.8  1976.9   396.9 1979.08   462.1 1987.54   478.4 1991.38
   484.9 1993.69   504.4 2005.01   514.2 2011.42   527.2 2017.63     537 2020.38
#Mann= 6 ,-1 , 0
       0     .06       0  137.25     .12       0  184.75     .08       0
  235.87     .12       0   240.6    .045       0   258.7     .12       0
#XS Ineff= 2 , 0
          231.82 1981.01
Permanent Ineff=
       F       F
Bank Sta=240.6,258.7
XS Rating Curve= 0 ,0
Exp/Cntr=0.3,0.1

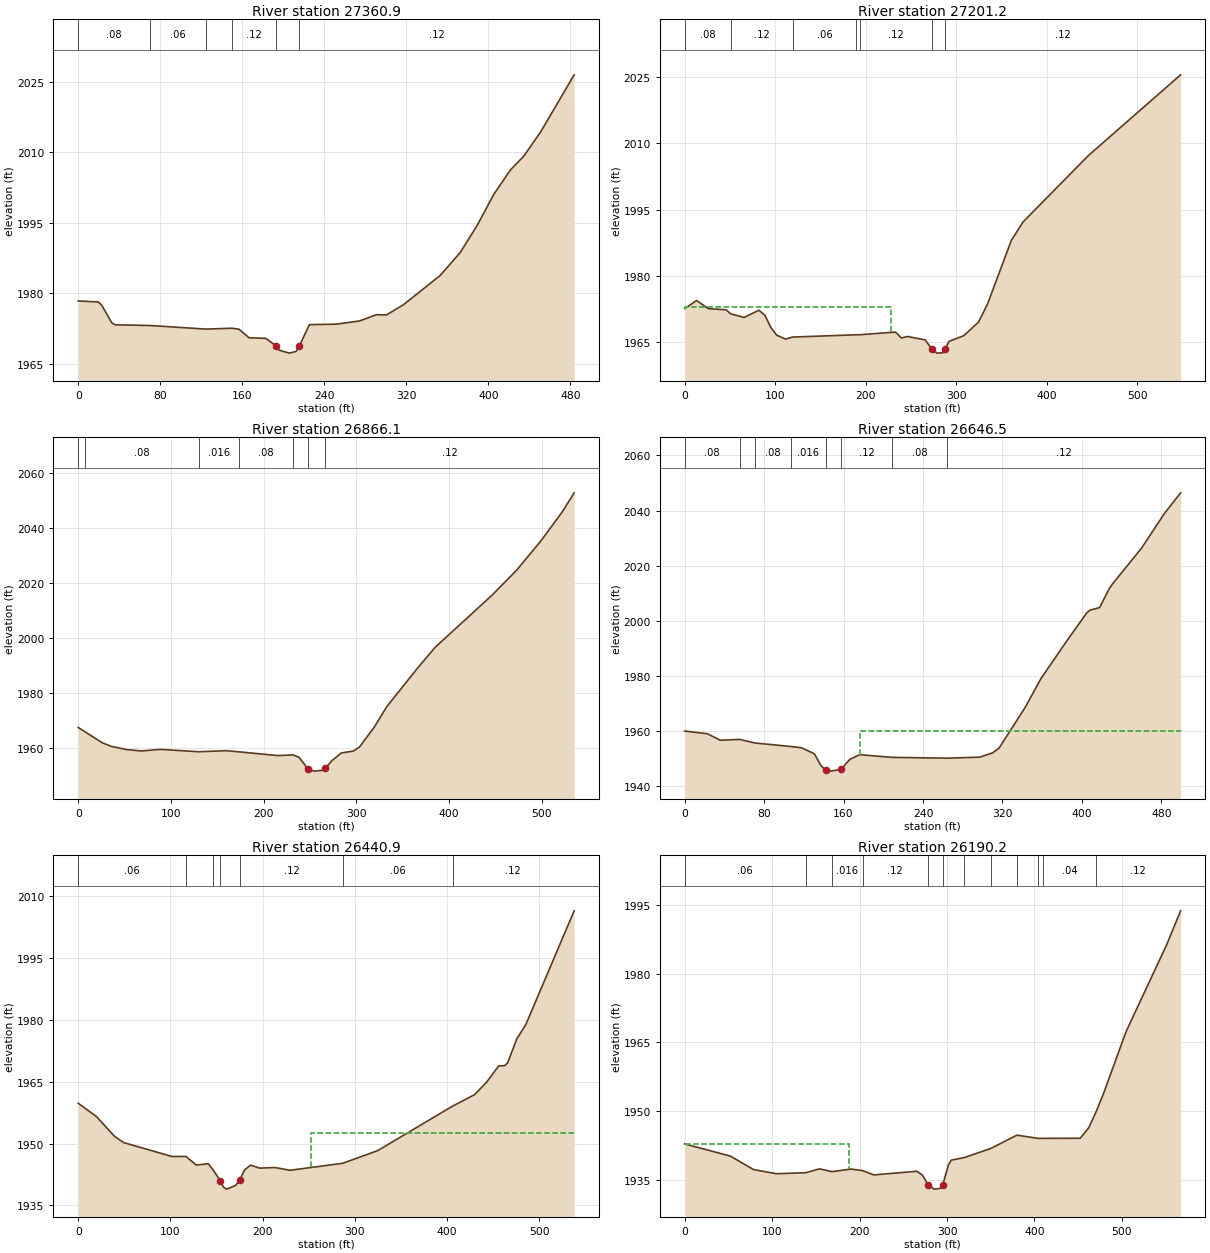
Type RM Length L Ch R = 1 ,27360.9 ,162.2,159.6,157.4
XS GIS Cut Line= 2
      2038110.18      282437.869      2038320.25      282873.632
#Sta/Elev= 30
       0 1978.38    19.6 1978.16    22.9 1977.49    32.7 1973.74      36  1973.3
   69.851973.152  125.021972.383  150.151972.577   156.9 1972.35   166.7 1970.54
     183 1970.41   192.8 1968.85   196.1 1967.89   205.9 1967.27   212.5 1967.62
   215.7 1968.76   225.5 1973.33   251.7 1973.44   274.6 1974.12   290.9 1975.45
   300.7  1975.4   317.1 1977.55     353 1983.78   372.6 1988.67     389 1994.39
   405.3 2001.03   421.6 2006.26   434.7 2009.22   451.1 2014.36   483.8 2026.52
#Mann= 6 ,-1 , 0
       0     .08       0   69.85     .06       0  125.02     .08       0
  150.15     .12       0   192.8    .045       0   215.7     .12       0
Bank Sta=192.8,215.7
XS Rating Curve= 0 ,0
Exp/Cntr=0.3,0.1

Type RM Length L Ch R = 1 ,27201.2 ,335.7,335.2,334.5
XS GIS Cut Line= 2
     2037932.663      282476.497     2038210.441      282948.719
#Sta/Elev= 30
       0 1972.55    13.1  1974.4    26.2 1972.55    45.9 1972.28   50.761971.384
    65.6 1970.56      82  1972.2    88.6 1971.07    95.1 1968.33   101.7 1966.52
   111.5 1965.66   119.31966.113  189.661966.625   193.3 1966.64   232.9 1967.24
   239.5 1965.89     246 1966.25   265.7 1965.47     273 1963.42   278.8 1962.47
   285.4 1962.56     288 1963.51     292 1965.14   308.4 1966.43   324.8 1969.54
   334.6 1973.62   360.9 1988.03     374 1992.24   446.2 2007.29   547.9 2025.55
#Mann= 7 ,-1 , 0
       0     .08       0   50.76     .12       0   119.3     .06       0
  189.66     .08       0   193.3     .12       0     273    .045       0
     288     .12       0
#XS Ineff= 2 , 0
          228.41 1972.84
Permanent Ineff=
       F       F
Bank Sta=273,288
XS Rating Curve= 0 ,0
Exp/Cntr=0.3,0.1

Type RM Length L Ch R = 1 ,26866.1 ,218.3,219.6,219.7
XS GIS Cut Line= 2
     2037627.108      282604.969     2037903.149      283063.303
#Sta/Elev= 30
       0 1967.59    7.391966.002    26.1 1961.99    35.9  1960.7    52.2 1959.55
    68.5 1959.04    88.1 1959.63   130.1 1958.77   159.9 1959.15  173.491958.733
   215.3 1957.38  232.151957.615   238.2 1956.75     248 1952.53   254.5 1951.73
   264.3 1952.07   266.7 1952.84     274 1955.61   283.8 1958.32   296.9 1959.03
   303.4 1960.47   319.7 1967.87   332.8  1975.1   365.4 1988.86     385 1996.66
     447 2015.78     473 2024.71   499.2 2035.33     522 2045.78     535 2052.76
#Mann= 7 ,-1 , 0
       0     .06       0    7.39     .08       0   130.1    .016       0
  173.49     .08       0  232.15     .12       0     248    .045       0
   266.7     .12       0
Bank Sta=248,266.7
XS Rating Curve= 0 ,0
Exp/Cntr=0.3,0.1

Type RM Length L Ch R = 1 ,26646.5 ,195.3,205.6,213.4
XS GIS Cut Line= 2
     2037472.594      282724.761     2037722.594      283157.053
#Sta/Elev= 30
       0 1959.94    22.8 1958.96    35.9  1956.6   55.351956.896   70.831955.591
  106.981954.322   117.5 1953.87   130.6 1951.69   137.1 1947.46   142.2 1945.61
   146.9 1945.38   157.2    1946   166.5 1949.68   176.2 1951.35  209.121950.374
  263.881950.085     297 1950.45   310.1 1952.03   316.6 1953.75   342.7 1968.42
     359 1979.12   385.1 1992.83   404.7 2002.74     408 2003.82   417.8 2004.76
   427.6 2011.68   430.8 2013.34   460.2 2026.43   483.1 2038.94   499.4 2046.44
#Mann= 8 ,-1 , 0
       0     .08       0   55.35     .06       0   70.83     .08       0
  106.98    .016       0   142.2    .045       0   157.2     .12       0
  209.12     .08       0  263.88     .12       0
#XS Ineff= 2 , 0
                          176.14         1959.87
Permanent Ineff=
       F       F
Bank Sta=142.2,157.2
XS Rating Curve= 0 ,0
Exp/Cntr=0.3,0.1

Type RM Length L Ch R = 1 ,26440.9 ,252.9,250.7,249
XS GIS Cut Line= 3
     2037345.858      282736.914     2037387.524      283141.428
     2037469.121      283243.858
#Sta/Elev= 30
       0 1959.76    19.7 1956.54    39.4 1951.74    49.2 1950.23   101.7 1946.84
  116.811946.869   127.9 1944.78     141 1945.09   146.1 1943.64   154.1 1940.98
   157.4 1939.45   160.7 1938.94   170.5  1939.8   175.2 1941.21   180.4 1943.62
   186.9 1944.76   196.8 1944.03   213.2 1944.18   229.6 1943.51  286.971945.216
   324.7 1948.28  405.751959.051   429.6 1961.83   442.7 1964.86   455.8  1968.8
   462.3 1968.87   465.6 1969.59   475.4 1975.35   485.2 1978.82   537.6  2006.4
#Mann= 7 ,-1 , 0
       0     .06       0  116.81    .016       0   146.1     .12       0
   154.1    .045       0   175.2     .12       0  286.97     .06       0
  405.75     .12       0
#XS Ineff= 2 , 0
                          252.27         1952.62
Permanent Ineff=
       F       F
Bank Sta=154.1,175.2
XS Rating Curve= 0 ,0
Exp/Cntr=0.3,0.1

Type RM Length L Ch R = 1 ,26190.2 ,288.3,296.9,304.2
XS GIS Cut Line= 2
      2037092.66      282739.004     2037208.705      283294.205
#Sta/Elev= 30
       0 1942.87    52.5 1940.19    78.7 1937.27   104.9 1936.36  138.61 1936.58
   154.1 1937.42  168.781936.806   190.2 1937.38   203.41937.033   216.4  1936.1
   265.6  1936.9   272.1 1936.02   278.4 1933.96   285.2    1933   291.8 1933.14
   295.1 1933.89   301.6 1938.27   304.9 1939.32  319.661939.875  349.84 1941.85
  380.021944.778  404.31 1944.06  410.191944.078   452.4  1944.1   462.3 1946.44
  470.541949.884   478.7 1953.69   504.9  1967.4   550.8 1986.12   567.2 1993.71
#Mann= 12 ,-1 , 0
       0     .06       0  138.61     .12       0  168.78    .016       0
   203.4     .12       0   278.4    .045       0   295.1     .12       0
  319.66     .08       0  349.84     .06       0  380.02     .08       0
  404.31     .06       0  410.19     .04       0  470.54     .12       0
#XS Ineff= 2 , 0
          188.35 1942.84
Permanent Ineff=
       F       F
Bank Sta=278.4,295.1
XS Rating Curve= 0 ,0
Exp/Cntr=0.3,0.1