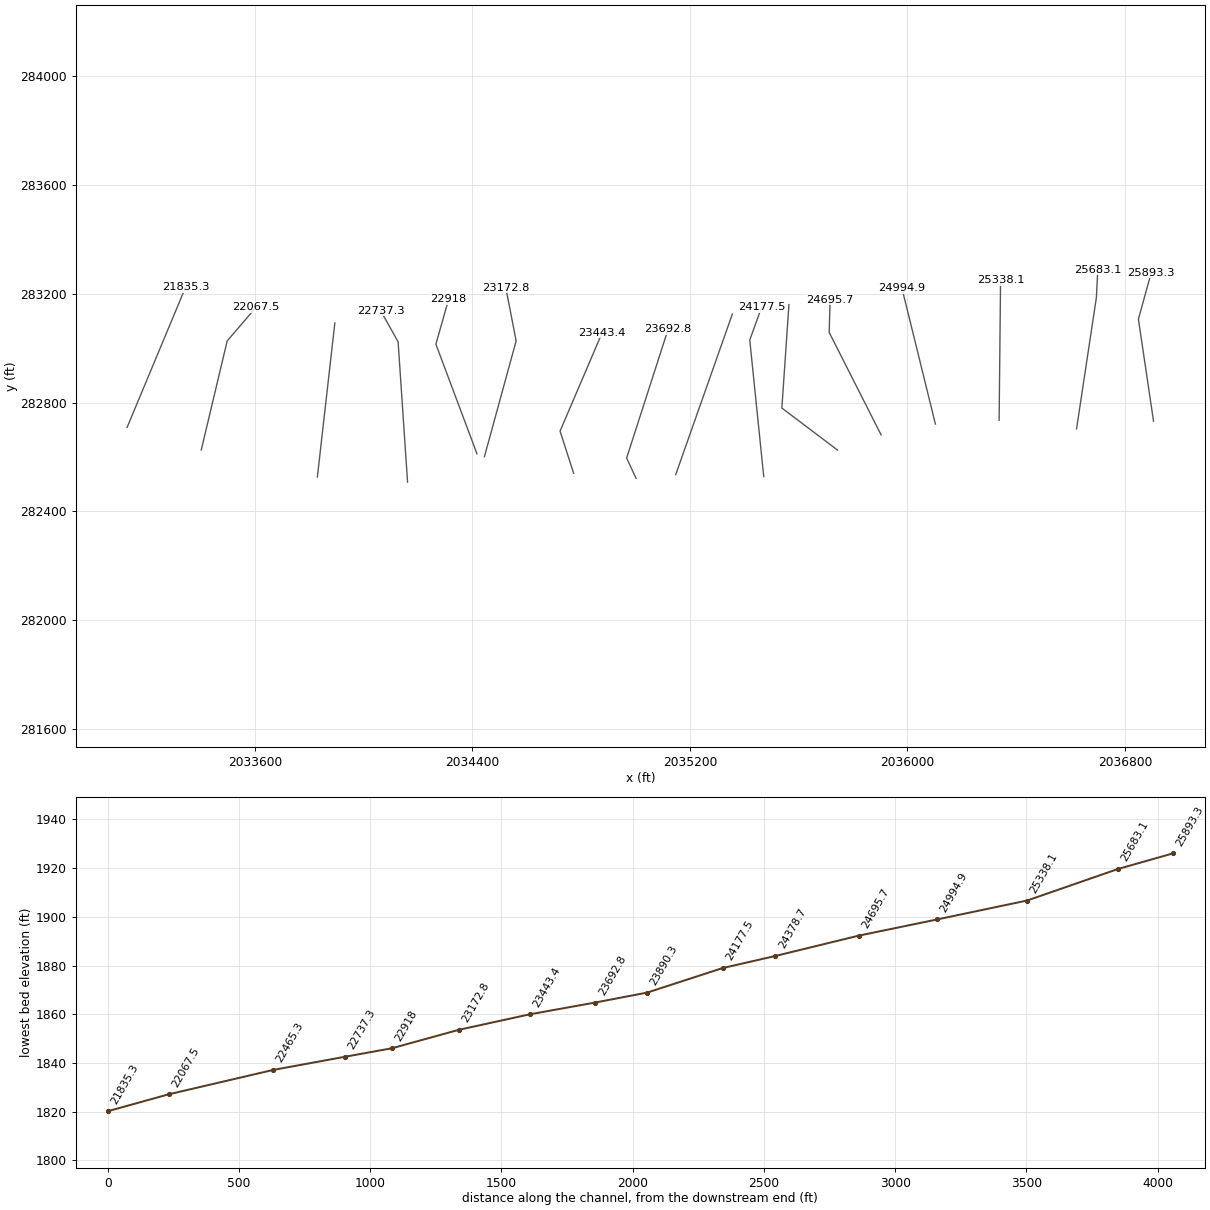
HEC-RAS study LICKCK1.prj: LICKCK1

--- LICKCK1.g01 (geometry) --- (continued)

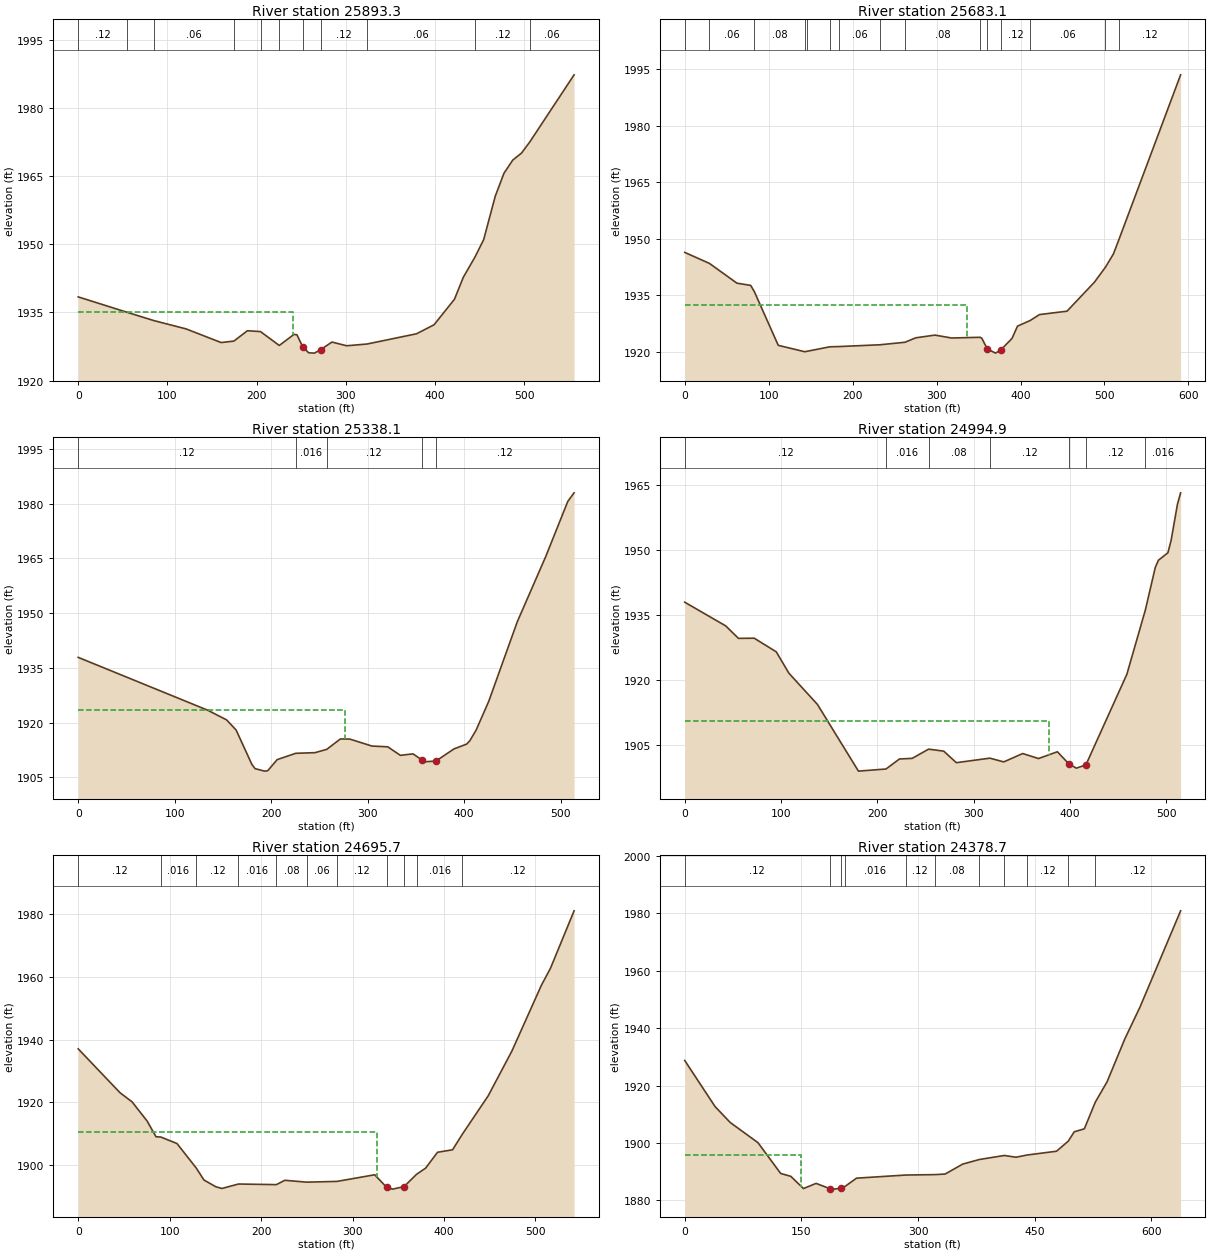
Type RM Length L Ch R = 1 ,25893.3 ,216.5,210.1,203
XS GIS Cut Line= 3
     2036904.885      282731.705      2036849.33      283106.705
     2036896.205      283276.844
#Sta/Elev= 30
       0 1938.42   54.951935.016   84.811933.199   120.9 1931.37   160.1 1928.37
  174.391928.688   189.6 1930.97  204.25 1930.78  225.271927.727   241.8 1930.16
   245.1 1930.08   251.6  1927.4   258.2 1926.12   264.7 1926.04   271.8 1926.83
   284.3 1928.48   300.7 1927.66  323.691928.046   379.1  1930.3   398.7 1932.28
   421.6 1937.91   431.4 1942.71   444.8 1947.28   454.3 1951.03   467.3  1960.6
   477.1 1965.66   486.9 1968.53   496.7 1970.08  506.071972.556   555.6  1987.3
#Mann= 11 ,-1 , 0
       0     .12       0   54.95     .08       0   84.81     .06       0
  174.39     .12       0  204.25    .016       0  225.27     .12       0
   251.6    .045       0   271.8     .12       0  323.69     .06       0
   444.8     .12       0  506.07     .06       0
#XS Ineff= 2 , 0
          240.34 1935.16
Permanent Ineff=
       F       F
Bank Sta=251.6,271.8
XS Rating Curve= 0 ,0
Exp/Cntr=0.3,0.1

Type RM Length L Ch R = 1 ,25683.1 ,341.4,345,347.9
XS GIS Cut Line= 3
     2036621.899      282703.928     2036694.816      283186.567
     2036700.024      283288.997
#Sta/Elev= 30
       0 1946.38   29.441943.454    62.2  1938.2    78.6 1937.61   83.061935.886
   111.4 1921.68   142.8 1919.99  145.98 1920.11  172.681921.287  184.24 1921.36
  232.421921.828   262.31922.496   275.2 1923.68   298.1  1924.4   317.8 1923.63
  351.921923.816   353.8  1923.6   360.4 1920.73   370.2 1919.61   376.7 1920.51
   389.8  1923.5   396.4 1926.78  411.661928.303   422.6 1929.86   455.4 1930.76
   488.1 1938.48  501.151942.448   510.6 1945.94   517.71950.085   590.7 1993.57
#Mann= 15 ,-1 , 0
       0     .08       0   29.44     .06       0   83.06     .08       0
   142.8     .06       0  145.98     .12       0  172.68     .08       0
  184.24     .06       0  232.42    .016       0   262.3     .08       0
  351.92     .12       0   360.4    .045       0   376.7     .12       0
  411.66     .06       0  501.15     .08       0   517.7     .12       0
#XS Ineff= 2 , 0
           335.8 1932.47
Permanent Ineff=
       F       F
Bank Sta=360.4,376.7
XS Rating Curve= 0 ,0
Exp/Cntr=0.3,0.1

Type RM Length L Ch R = 1 ,25338.1 ,337.3,343.2,348.5
XS GIS Cut Line= 2
     2036337.177      282735.178     2036342.385      283249.067
#Sta/Elev= 30
       0 1937.87   134.2 1923.39   153.8 1920.74   163.7 1917.94     180 1908.53
   183.3 1907.38   193.1  1906.7   196.4 1906.81   206.2 1909.85  225.431911.582
   245.5 1911.76  257.651912.675   271.7 1915.52   281.5 1915.48   304.4 1913.57
   320.8 1913.36   333.9 1911.02     347 1911.43   355.8 1909.83   360.1 1909.28
   370.8 1909.47   389.5  1912.8   402.6 1914.11   405.9 1915.05   412.4 1917.95
   425.5 1925.86     455  1947.6   484.5 1965.48   507.4 1980.61   513.9 1982.95
#Mann= 5 ,-1 , 0
       0     .12       0  225.43    .016       0  257.65     .12       0
   355.8    .045       0   370.8     .12       0
#XS Ineff= 2 , 0
          276.99 1923.44
Permanent Ineff=
       F       F
Bank Sta=355.8,370.8
XS Rating Curve= 0 ,0
Exp/Cntr=0.3,0.1

Type RM Length L Ch R = 1 ,24994.9 ,292.9,299.2,302.9
XS GIS Cut Line= 2
     2036102.802      282721.289     2035979.538      283221.289
#Sta/Elev= 30
       0    1938    42.6 1932.51    55.8 1929.63    72.2 1929.67    95.1 1926.51
   108.2 1921.57   137.8 1914.36   180.4 1898.92  209.031899.411     223 1901.73
   236.2 1901.87  253.291904.007     269 1903.54   282.1 1900.87  316.931901.923
   331.3 1901.05     351 1902.99   367.4 1901.83     387  1903.4     399 1900.59
   406.7 1899.61   416.6 1900.35   459.2 1921.34  478.42 1936.23   488.7 1946.06
     492 1947.72   501.8 1949.43   505.1 1952.27   511.7 1960.65     515  1963.3
#Mann= 7 ,-1 , 0
       0     .12       0  209.03    .016       0  253.29     .08       0
  316.93     .12       0     399    .045       0   416.6     .12       0
  478.42    .016       0
#XS Ineff= 2 , 0
          378.41 1910.59
Permanent Ineff=
       F       F
Bank Sta=399,416.6
XS Rating Curve= 0 ,0
Exp/Cntr=0.3,0.1

Type RM Length L Ch R = 1 ,24695.7 ,307.2,317,325.7
XS GIS Cut Line= 3
     2035903.149      282681.358     2035712.177      283058.094
     2035715.649      283177.886
#Sta/Elev= 30
       0 1937.02    45.8    1923    58.9 1920.11    75.3 1914.01    85.1 1908.96
   90.121908.906     108 1906.81  129.121898.972   137.5 1895.16   150.6    1893
   157.2 1892.47  175.261893.889  216.711893.696   225.9 1895.08  249.821894.487
  282.941894.724   324.2 1896.84   337.2 1892.86   343.8 1892.26   356.3 1893.07
  369.981896.995   379.8 1898.95   392.9 1904.02   409.3 1904.81  420.151909.842
   448.3 1922.04   474.2 1936.32   506.6  1957.4   516.3 1962.68   542.2 1981.06
#Mann= 11 ,-1 , 0
       0     .12       0   90.12    .016       0  129.12     .12       0
  175.26    .016       0  216.71     .08       0  249.82     .06       0
  282.94     .12       0   337.2    .045       0   356.3     .12       0
  369.98    .016       0  420.15     .12       0
#XS Ineff= 2 , 0
          326.42 1910.42
Permanent Ineff=
       F       F
Bank Sta=337.2,356.3
XS Rating Curve= 0 ,0
Exp/Cntr=0.3,0.1

Type RM Length L Ch R = 1 ,24378.7 ,218.5,201.2,182.9
XS GIS Cut Line= 3
     2035743.051      282625.542      2035538.19      282780.056
     2035564.231      283160.264
#Sta/Elev= 30
       0 1928.73      39 1912.68    58.5 1907.13    94.2  1900.1   123.4 1889.37
   136.4 1888.38   152.7 1884.12   168.9 1885.92   186.3 1884.11   191.6 1883.92
   201.3 1884.27  206.151884.864   220.9 1887.74  284.151888.825   321.81888.975
   334.8 1889.17   357.6 1892.65  378.871894.234     4111895.643     426 1895.03
  440.231895.801   478.1 1897.12  493.251900.637   500.9 1903.89   513.9 1904.93
  527.961914.201   543.2 1921.34     566 1936.28   585.6 1947.42   637.7 1980.86
#Mann= 11 ,-1 , 0
       0     .12       0   186.3    .045       0   201.3     .12       0
  206.15    .016       0  284.15     .12       0   321.8     .08       0
  378.87     .06       0     411     .08       0  440.23     .12       0
  493.25    .016       0  527.96     .12       0
#XS Ineff= 2 , 0
          150.14  1895.9
Permanent Ineff=
       F       F
Bank Sta=186.3,201.3
XS Rating Curve= 0 ,0
Exp/Cntr=0.3,0.1

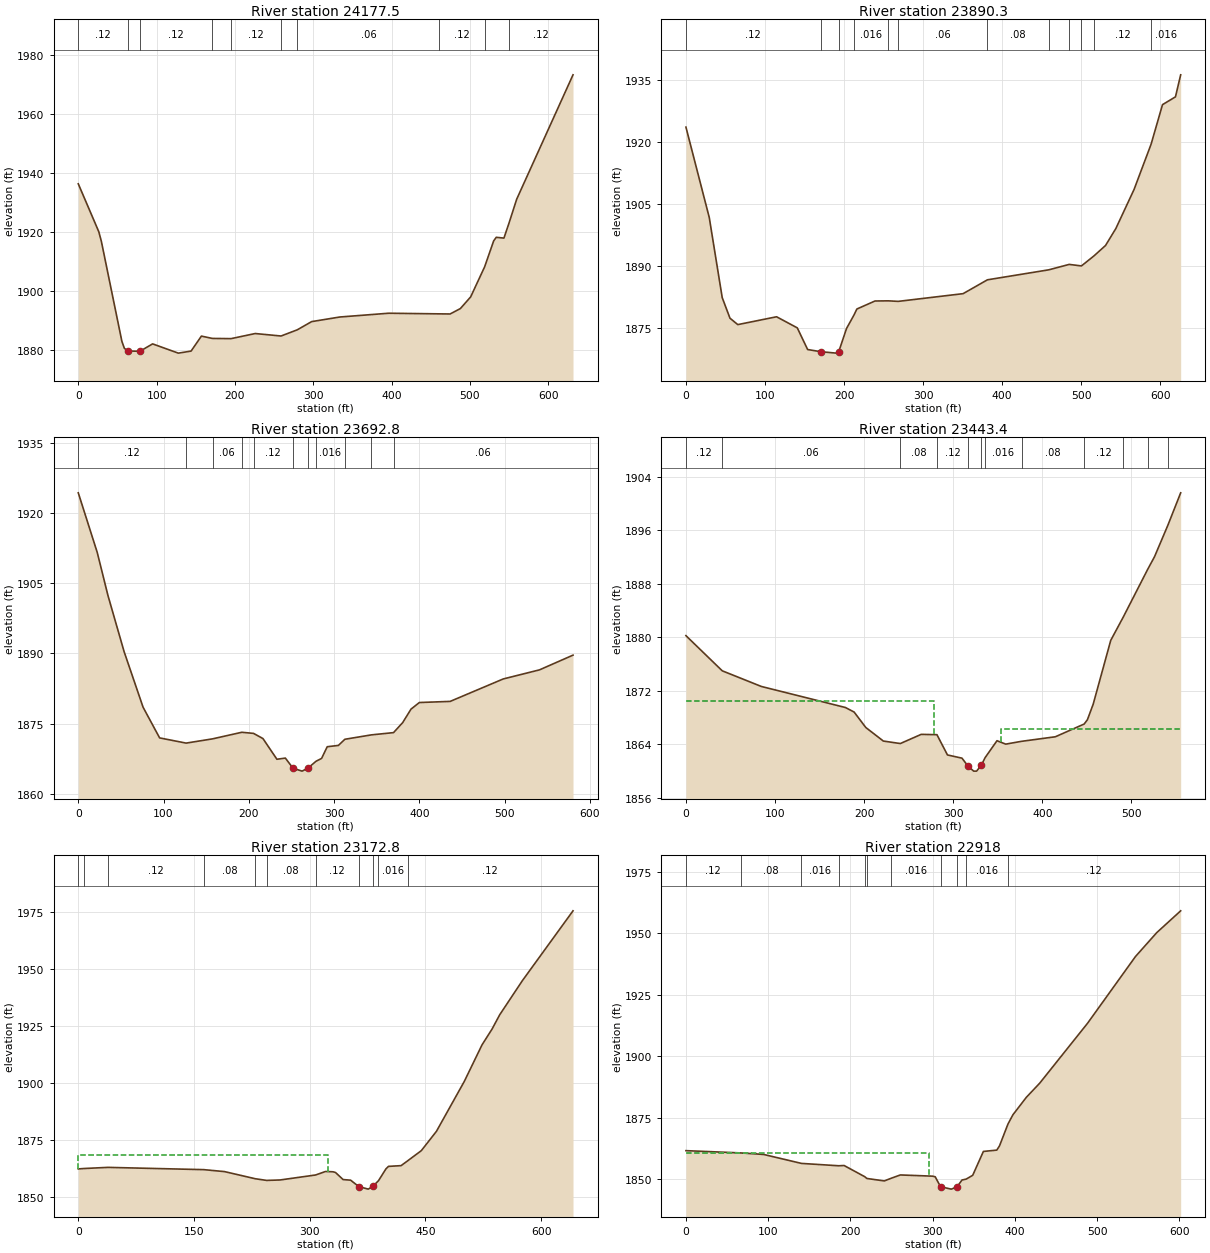
Type RM Length L Ch R = 1 ,24177.5 ,297.2,287.2,277.3
XS GIS Cut Line= 3
     2035471.566      282528.501     2035420.134      283030.056
     2035463.537      283149.848
#Sta/Elev= 30
       0 1936.34    26.2  1920.1    29.5 1916.81    55.7 1882.92    58.9 1880.57
    63.7 1879.68    78.7 1879.59    94.9 1882.09   127.7 1878.96     144 1879.65
   157.2 1884.73   171.21883.942  195.05 1883.87   225.9  1885.6  258.881884.761
  279.681886.874   297.9 1889.64   333.9  1891.2   396.2 1892.48  460.931892.268
   474.7 1892.23   487.8 1894.06   500.9 1898.01  518.721908.172   530.3    1917
   533.6 1918.21   543.4 1917.95  549.72  1922.9   559.7 1931.13   631.6 1973.28
#Mann= 10 ,-1 , 0
       0     .12       0    63.7    .045       0    78.7     .12       0
   171.2    .016       0  195.05     .12       0  258.88     .08       0
  279.68     .06       0  460.93     .12       0  518.72    .016       0
  549.72     .12       0
Bank Sta=63.7,78.7
XS Rating Curve= 0 ,0
Exp/Cntr=0.3,0.1

Type RM Length L Ch R = 1 ,23890.3 ,196.5,197.5,197.8
XS GIS Cut Line= 2
     2035147.941      282535.525     2035356.274      283125.803
#Sta/Elev= 30
       0 1923.66    29.5 1901.77    45.9 1882.35    55.7 1877.36    65.6  1875.8
   114.7  1877.7   140.9 1875.01     154 1869.76   170.5 1869.24   190.1 1868.89
   193.4 1869.27   203.2 1874.86  212.681878.142   216.3 1879.58   239.2 1881.52
  256.031881.561  268.621881.431   350.7  1883.3  381.481886.656  458.951889.071
  484.911890.387  500.461890.024  516.231892.441   530.9 1894.97     544 1899.09
     567 1908.54  588.591919.532     603  1929.1   619.4 1930.99     626 1936.33
#Mann= 12 ,-1 , 0
       0     .12       0   170.5    .045       0   193.4     .12       0
  212.68    .016       0  256.03     .12       0  268.62     .06       0
  381.48     .08       0  458.95     .06       0  484.91     .12       0
  500.46     .08       0  516.23     .12       0  588.59    .016       0
Bank Sta=170.5,193.4
XS Rating Curve= 0 ,0
Exp/Cntr=0.3,0.1

Type RM Length L Ch R = 1 ,23692.8 ,251.8,249.4,247.5
XS GIS Cut Line= 3
     2035002.108      282521.636     2034967.385      282596.289
     2035120.163      283070.247
#Sta/Elev= 30
       0 1924.37    22.2 1911.64    34.8 1902.41    53.8 1890.36      76  1878.5
    95.4 1871.93   126.51870.816  157.541871.725  191.811873.134  205.571872.894
   216.6 1871.79     233 1867.36   242.9 1867.61   251.9 1865.44   262.5 1864.82
   269.1 1865.42  278.93 1866.94   285.4 1867.54     292 1870.04   305.1 1870.32
  312.711871.636  343.741872.574  369.771873.061   380.5  1875.2   390.3 1878.09
   400.1  1879.5   436.2 1879.74   498.4 1884.54     541 1886.49   580.3 1889.64
#Mann= 11 ,-1 , 0
       0     .12       0   126.5     .08       0  157.54     .06       0
  191.81     .08       0  205.57     .12       0   251.9    .045       0
   269.1     .12       0  278.93    .016       0  312.71     .12       0
  343.74     .08       0  369.77     .06       0
Bank Sta=251.9,269.1
XS Rating Curve= 0 ,0
Exp/Cntr=0.3,0.1

Type RM Length L Ch R = 1 ,23443.4 ,267.3,270.5,273.7
XS GIS Cut Line= 3
     2034772.565      282540.473     2034722.594      282695.247
     2034877.108      283056.358
#Sta/Elev= 30
       0 1880.25   40.75 1874.99    84.6 1872.65     179  1869.5   188.8 1868.82
   201.9 1866.51   221.6 1864.48  240.681864.107   264.1 1865.48  281.771865.432
   293.6  1862.4   309.9 1861.92   316.5 1860.76     323 1859.98   326.3 1859.98
  331.66 1860.88  335.881862.003   349.2 1864.53     359 1864.02  376.82 1864.44
   414.7 1865.12  447.051867.026   450.7 1867.67   457.2    1870   476.9 1879.55
  490.961883.034  518.391890.176     526 1892.05  541.011896.763   555.4 1901.62
#Mann= 12 ,-1 , 0
       0     .12       0   40.75     .06       0  240.68     .08       0
  281.77     .12       0   316.5    .045       0  331.66     .12       0
  335.88    .016       0  376.82     .08       0  447.05     .12       0
  490.96     .08       0  518.39     .12       0  541.01     .08       0
#XS Ineff= 2 , 0
          278.69 1870.48  353.69         1866.28
Permanent Ineff=
       F       F
Bank Sta=316.5,331.66
XS Rating Curve= 0 ,0
Exp/Cntr=0.3,0.1

Type RM Length L Ch R = 1 ,23172.8 ,240.5,254.9,268.6
XS GIS Cut Line= 3
      2034444.44      282601.237     2034561.135      283026.844
     2034522.941      283223.025
#Sta/Elev= 30
       0 1862.45    7.821862.628   38.451863.123  162.671862.127   189.6 1861.27
  229.361858.154  244.131857.423   261.5 1857.61  307.571859.791   320.4 1861.32
   330.2 1861.19   333.4 1860.88   343.2 1857.79     353 1857.52   363.7 1854.69
   375.9 1853.61   382.5 1855.07  389.021857.259   398.8 1862.49   402.1 1863.56
   418.4 1863.88  426.871865.985   444.6 1870.44   464.2 1878.89   500.3 1900.71
   523.2 1916.65   536.3 1923.62   546.2 1929.85   575.6 1944.78   641.2  1975.3
#Mann= 11 ,-1 , 0
       0     .06       0    7.82     .08       0   38.45     .12       0
  162.67     .08       0  229.36     .12       0  244.13     .08       0
  307.57     .12       0   363.7    .045       0   382.5     .12       0
  389.02    .016       0  426.87     .12       0
#XS Ineff= 2 , 0
          324.15 1868.54
Permanent Ineff=
       F       F
Bank Sta=363.7,382.5
XS Rating Curve= 0 ,0
Exp/Cntr=0.3,0.1

Type RM Length L Ch R = 1 ,22918   ,186.9,180.7,173.6
XS GIS Cut Line= 3
     2034417.038      282611.914     2034265.996      283014.692
     2034312.871      283179.622
#Sta/Elev= 30
       0 1861.67   66.431860.749    94.5 1860.13  140.491856.489  185.931855.525
   192.3 1855.64  217.471851.081  220.071850.368   241.2 1849.37  249.021850.384
   260.7  1851.8   299.8 1851.31   303.1 1851.06   309.6 1847.02   322.6 1846.04
   329.5 1846.89   335.7 1849.74  340.711850.108   348.7 1851.65   361.7 1861.35
     378 1861.89   381.3 1863.62  391.571872.464   397.6 1876.24   413.9 1883.32
   430.2 1889.09   488.4 1913.44   546.6 1940.52   572.5 1950.24   601.6  1959.1
#Mann= 11 ,-1 , 0
       0     .12       0   66.43     .08       0  140.49    .016       0
  185.93     .08       0  217.47     .12       0  220.07     .04       0
  249.02    .016       0   309.6    .045       0   329.5     .12       0
  340.71    .016       0  391.57     .12       0
#XS Ineff= 2 , 0
          295.31 1860.64
Permanent Ineff=
       F       F
Bank Sta=309.6,329.5
XS Rating Curve= 0 ,0
Exp/Cntr=0.3,0.1

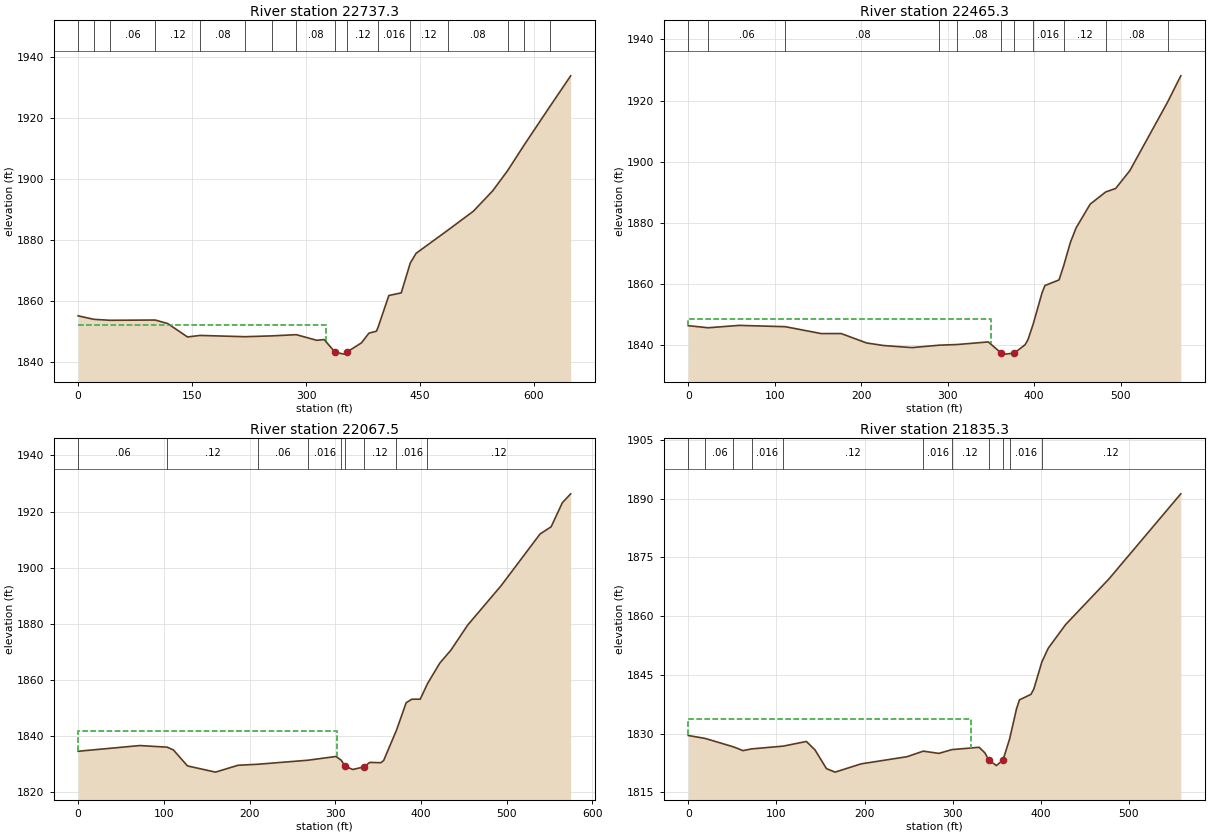
Type RM Length L Ch R = 1 ,22737.3 ,275.8,272,267.6
XS GIS Cut Line= 3
      2034161.83      282507.747     2034127.108      283023.372
     2034062.871      283137.955
#Sta/Elev= 30
       0 1855.06   20.581853.919   42.041853.602  101.251853.685   117.8 1852.54
   143.9 1848.14  160.461848.635  219.671848.222  254.93 1848.49  287.061848.888
     314 1847.04   323.8 1847.28  338.091843.127     350 1842.51     354 1843.22
   372.9 1846.22   382.7 1849.39   392.5 1850.02  394.541851.188   408.9 1861.72
   425.2 1862.59  437.061872.344   444.8 1875.56  486.111883.049     520 1889.32
   545.6 1896.04  565.151902.634  587.331911.182     6211923.724   648.2 1933.72
#Mann= 16 ,-1 , 0
       0     .12       0   20.58     .08       0   42.04     .06       0
  101.25     .12       0  160.46     .08       0  219.67     .12       0
  254.93    .016       0  287.06     .08       0  338.09    .045       0
     354     .12       0  394.54    .016       0  437.06     .12       0
  486.11     .08       0  565.15     .06       0  587.33     .08       0
     621     .06       0
#XS Ineff= 2 , 0
          326.14 1851.97
Permanent Ineff=
       F       F
Bank Sta=338.09,354
XS Rating Curve= 0 ,0
Exp/Cntr=0.3,0.1

Type RM Length L Ch R = 1 ,22465.3 ,400.3,397.8,395
XS GIS Cut Line= 2
     2033830.233      282526.844     2033894.469      283092.817
#Sta/Elev= 30
       0 1846.43   22.99 1845.74    58.9 1846.52  112.171846.096   153.9 1843.84
   176.8 1843.86   206.2 1840.78   225.9 1839.94   258.6 1839.26  290.541840.057
  311.191840.269     347 1841.12   362.2  1837.4   366.6 1837.13   377.2 1837.48
   389.6 1840.22   392.8 1841.81  398.831846.906   409.2 1857.21   412.5 1859.55
   428.8 1861.38  434.231866.089   441.9 1873.62   448.5 1878.37   464.8 1886.14
  482.751890.117   494.3 1891.27   510.7  1897.1  554.411919.537   569.6 1928.07
#Mann= 11 ,-1 , 0
       0     .12       0   22.99     .06       0  112.17     .08       0
  290.54    .016       0  311.19     .08       0   362.2    .045       0
   377.2     .12       0  398.83    .016       0  434.23     .12       0
  482.75     .08       0  554.41     .12       0
#XS Ineff= 2 , 0
          350.28 1848.74
Permanent Ineff=
       F       F
Bank Sta=362.2,377.2
XS Rating Curve= 0 ,0
Exp/Cntr=0.3,0.1

Type RM Length L Ch R = 1 ,22067.5 ,235.8,232.2,228.5
XS GIS Cut Line= 3
     2033403.149      282625.803     2033498.635      283026.844
     2033604.538      283150.108
#Sta/Elev= 30
       0 1834.57      72  1836.6  103.931836.027   111.2 1835.02   127.6 1829.34
   160.3 1827.13   186.5 1829.57     2101829.943  267.951831.364     301 1832.71
  307.031831.367  311.65 1829.21   320.6 1828.07   333.7 1829.02   340.3 1830.59
   353.4 1830.49   356.6 1831.32  371.481842.039   382.8 1851.87   389.4 1853.11
   399.2 1853.13  407.671858.645     422 1865.96     435 1870.59   454.5  1879.5
   493.5 1893.53     539 1911.98     552 1914.57     565 1923.11   574.8 1926.31
#Mann= 9 ,-1 , 0
       0     .06       0  103.93     .12       0     210     .06       0
  267.95    .016       0  307.03     .12       0  311.65    .045       0
   333.7     .12       0  371.48    .016       0  407.67     .12       0
#XS Ineff= 2 , 0
           301.7 1841.71
Permanent Ineff=
       F       F
Bank Sta=311.65,333.7
XS Rating Curve= 0 ,0
Exp/Cntr=0.3,0.1

Type RM Length L Ch R = 1 ,21835.3 ,415.8,423.1,429.3
XS GIS Cut Line= 2
      2033130.58      282709.136     2033345.858      283224.761
#Sta/Elev= 30
       0 1829.53   19.251828.777   51.261826.631    62.1 1825.67   71.841826.108
  107.781826.819     134 1828.01   143.8 1825.85   156.8 1821.07   166.6 1820.18
   196.1 1822.29   248.3 1824.12   266.7 1825.54   284.3 1824.96  299.131825.929
     330 1826.52   336.6 1825.09   340.8 1823.29   349.6 1821.86   357.1 1823.27
  364.611828.664   372.5 1836.42   375.8 1838.63   388.8 1840.03   392.1 1841.41
  401.111848.253   408.4  1851.8   428.1 1857.83   477.1 1869.44   558.8 1891.21
#Mann= 11 ,-1 , 0
       0     .08       0   19.25     .06       0   51.26     .08       0
   71.84    .016       0  107.78     .12       0   266.7    .016       0
  299.13     .12       0   340.8    .045       0   357.1     .12       0
  364.61    .016       0  401.11     .12       0
#XS Ineff= 2 , 0
          320.45 1833.76
Permanent Ineff=
       F       F
Bank Sta=340.8,357.1
XS Rating Curve= 0 ,0
Exp/Cntr=0.3,0.1