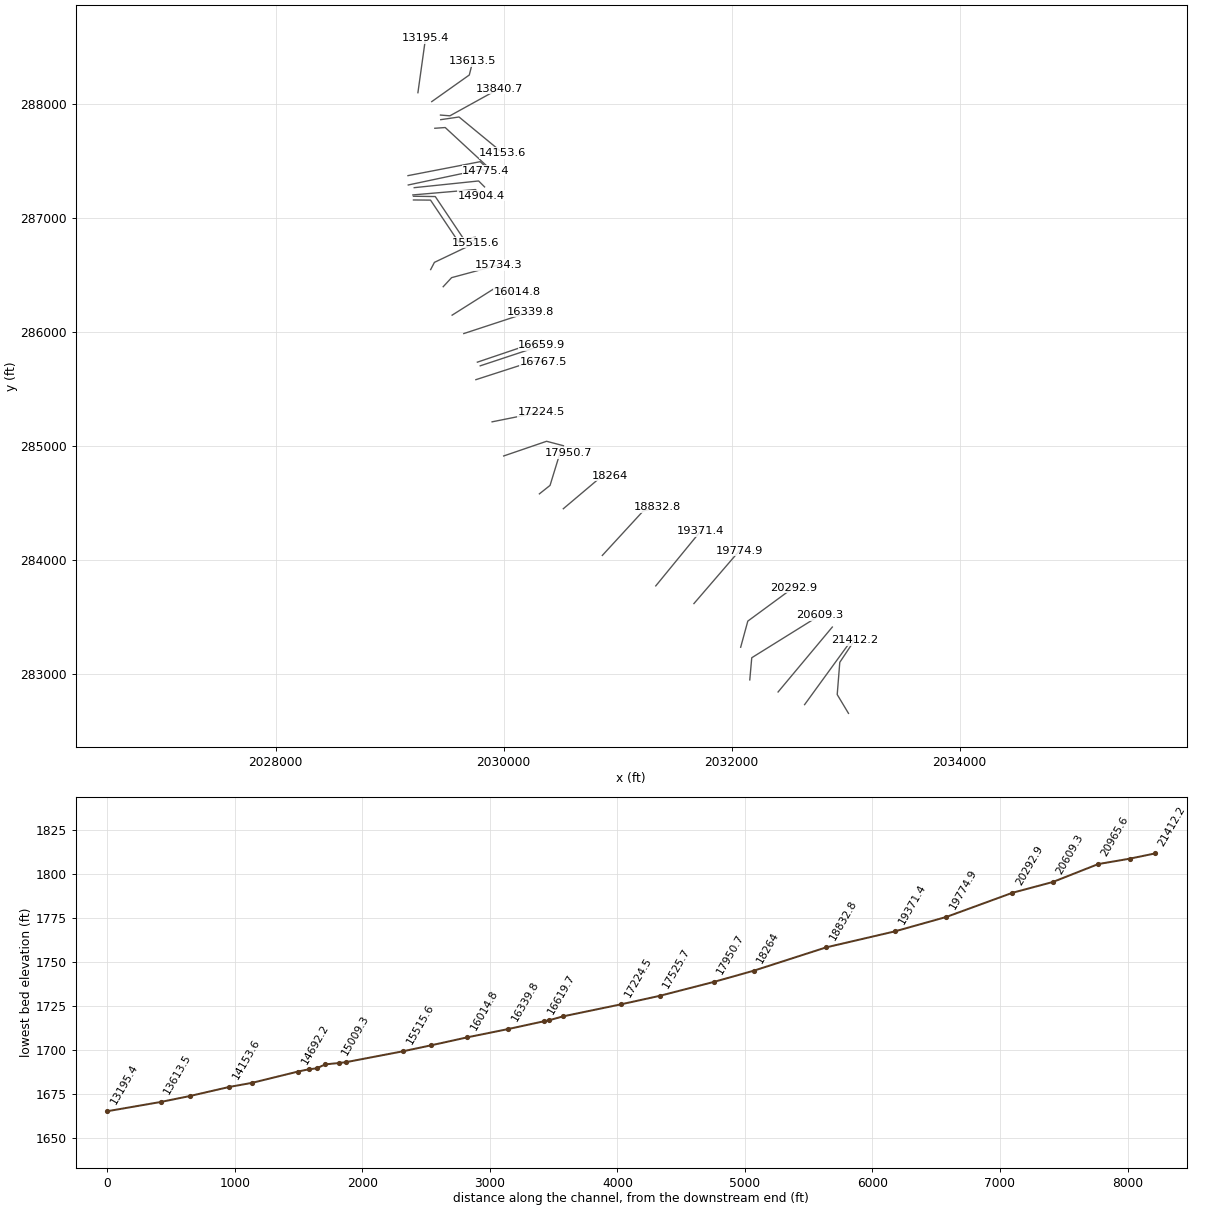
HEC-RAS study LICKCK1.prj: LICKCK1

--- LICKCK1.g01 (geometry) --- (continued)

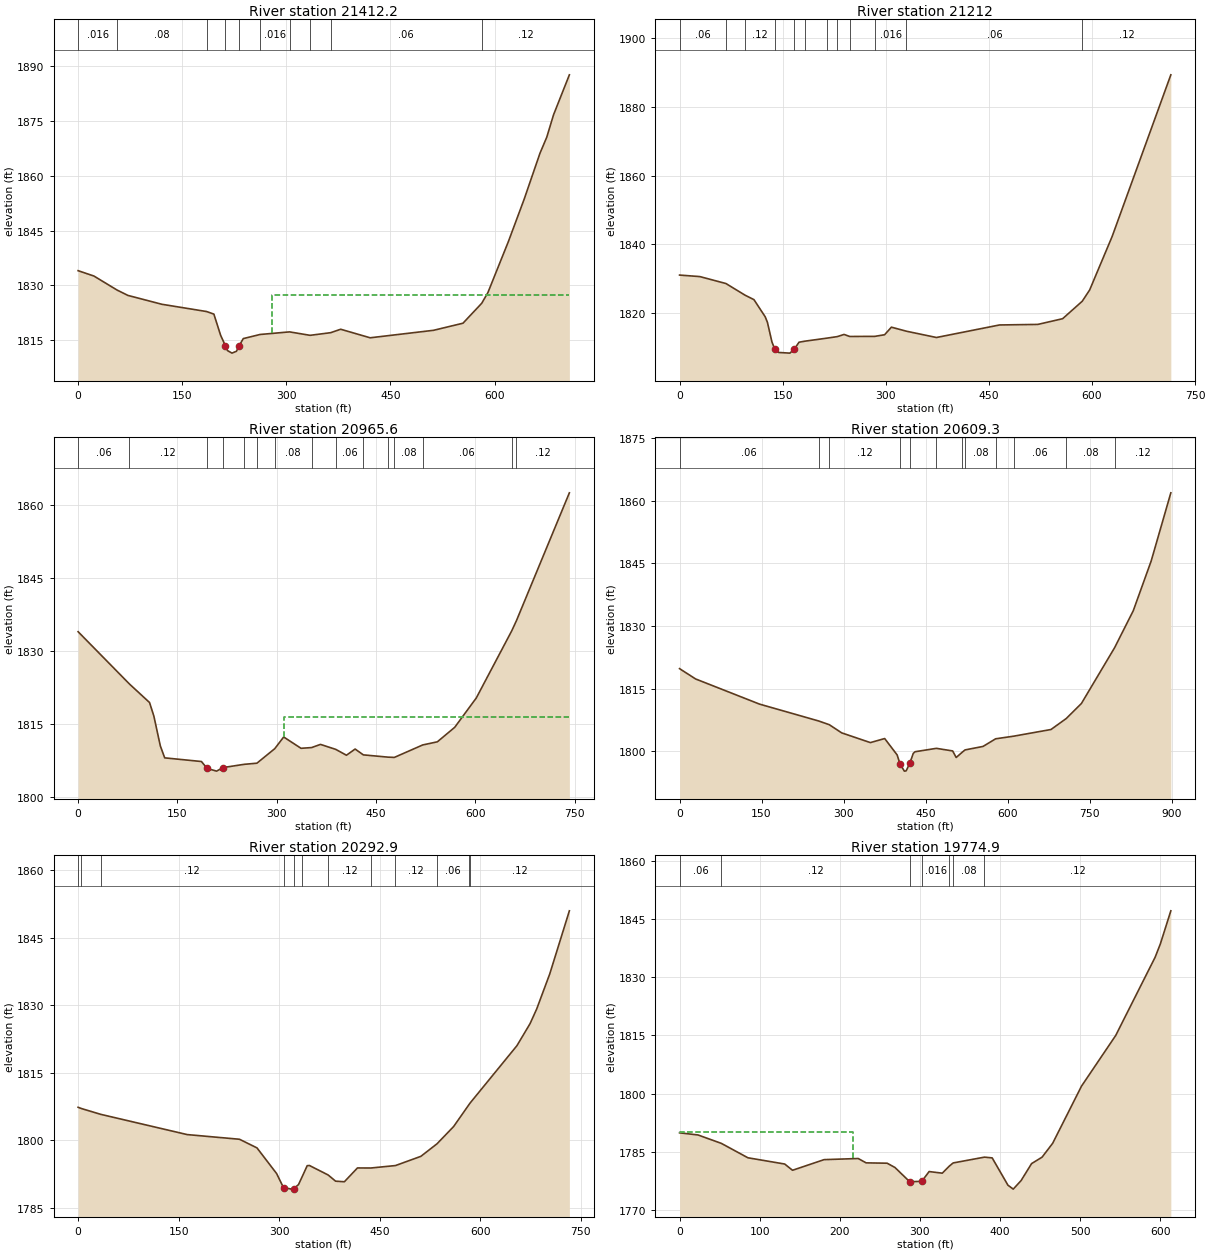
Type RM Length L Ch R = 1 ,21412.2 ,213.3,200.2,187.6
XS GIS Cut Line= 4
     2033024.301      282656.792     2032925.343      282821.723
     2032947.912      283104.709     2033076.384      283297.417
#Sta/Elev= 30
       0 1834.02    22.8 1832.55   56.151828.711    71.7 1827.25   120.6 1824.82
  185.091822.831   195.6 1822.13   205.4  1816.3   212.3 1813.43   215.2 1812.14
   221.7 1811.44   228.2 1811.96   231.5  1813.3     238 1815.42  262.091816.543
  304.631817.257  334.261816.315   363.91817.038   378.3 1817.98   420.8 1815.64
   512.1 1817.69   554.5 1819.63  581.491825.088   590.4 1828.01   619.8 1841.93
   642.6 1853.56   665.4 1866.16   675.2 1870.56     685 1876.71   707.8 1887.65
#Mann= 10 ,-1 , 0
       0    .016       0   56.15     .08       0  185.09     .12       0
   212.3    .045       0   231.5     .12       0  262.09    .016       0
  304.63     .12       0  334.26     .08       0   363.9     .06       0
  581.49     .12       0
#XS Ineff= 2 , 0
                          279.55         1827.26
Permanent Ineff=
       F       F
Bank Sta=212.3,231.5
XS Rating Curve= 0 ,0
Exp/Cntr=0.3,0.1

Type RM Length L Ch R = 1 ,21212   ,246.9,246.4,244.6
XS GIS Cut Line= 2
      2032639.26      282733.442     2033059.399      283311.567
#Sta/Elev= 30
       0 1831.11    29.5 1830.67   67.411828.657   95.391825.259   108.2 1823.98
   124.6 1818.99   127.8  1817.4   134.4 1811.68  138.64 1809.55   144.2 1808.63
   160.6 1808.44   167.2 1809.69   173.8 1811.61  182.221811.908  213.861812.777
  229.641813.243   239.3 1813.87   247.51813.276  284.021813.308   298.3 1813.78
   308.2 1815.98  330.131814.801   373.7 1812.98   465.5 1816.62   521.2 1816.78
   557.3 1818.44  585.76  1823.5   596.6 1826.78   629.4 1842.36   714.7 1889.27
#Mann= 12 ,-1 , 0
       0     .06       0   67.41     .08       0   95.39     .12       0
  138.64    .045       0   167.2     .12       0  182.22    .016       0
  213.86     .06       0  229.64     .08       0   247.5     .06       0
  284.02    .016       0  330.13     .06       0  585.76     .12       0
Bank Sta=138.64,167.2
XS Rating Curve= 0 ,0
Exp/Cntr=0.3,0.1

Type RM Length L Ch R = 1 ,20965.6 ,363.6,356.3,348.1
XS GIS Cut Line= 2
     2032406.621      282844.553     2032882.316      283413.997
#Sta/Elev= 30
       0 1833.98   77.611823.249   107.9 1819.46   114.4 1816.69   124.2 1810.56
   130.8 1808.11   186.3 1807.36   194.9 1805.94   209.2 1805.39     219 1806.12
  250.941806.786  270.051807.015  297.011809.995   310.5 1812.39   336.7 1810.07
  352.671810.221   366.1 1810.87  389.15 1809.85   405.3 1808.65   418.4 1809.92
   430.81808.724  468.041808.258  477.641808.203  520.581810.762   542.6  1811.4
   568.8 1814.37   601.4 1820.39  654.941834.159  662.021836.233     742 1862.46
#Mann= 15 ,-1 , 0
       0     .06       0   77.61     .12       0   194.9    .045       0
     219     .12       0  250.94     .08       0  270.05     .06       0
  297.01     .08       0  352.67    .016       0  389.15     .06       0
   430.8     .08       0  468.04     .06       0  477.64     .08       0
  520.58     .06       0  654.94     .08       0  662.02     .12       0
#XS Ineff= 2 , 0
                          311.36         1816.41
Permanent Ineff=
       F       F
Bank Sta=194.9,219
XS Rating Curve= 0 ,0
Exp/Cntr=0.3,0.1

Type RM Length L Ch R = 1 ,20609.3 ,313.1,316.3,318.9
XS GIS Cut Line= 3
     2032158.358      282950.455     2032175.719        283144.9
     2032772.941      283516.428
#Sta/Elev= 30
       0 1819.78    29.3 1817.31   146.4 1811.27  254.711807.222  273.961806.334
   296.6 1804.38     349 1802.05   375.2 1803.02     398 1799.09   403.1 1796.99
   411.1 1795.21   414.4 1795.26     421 1797.06   427.5 1799.47   430.8 1799.86
  469.681800.673   499.5 1800.05     506 1798.48  517.461799.792  522.241800.297
   555.1 1801.13  578.161802.959  611.361803.594   679.4 1805.19  707.281807.819
     735 1811.42  795.761824.805   829.9 1833.67   862.6 1845.57   898.6 1861.93
#Mann= 12 ,-1 , 0
       0     .06       0  254.71     .08       0  273.96     .12       0
   403.1    .045       0     421     .12       0  469.68    .016       0
  517.46     .12       0  522.24     .08       0  578.16     .12       0
  611.36     .06       0  707.28     .08       0  795.76     .12       0
Bank Sta=403.1,421
XS Rating Curve= 0 ,0
Exp/Cntr=0.3,0.1

Type RM Length L Ch R = 1 ,20292.9 ,512.9,518,520.9
XS GIS Cut Line= 3
     2032078.496      283236.914     2032140.996       283466.08
     2032540.302      283759.483
#Sta/Elev= 30
       0 1807.29    5.031807.009   33.861805.718   162.7 1801.22   240.8 1800.18
   266.9 1798.26   296.2 1792.55   306.5 1789.41     319 1789.09   321.5 1789.17
   328.8 1790.09   334.81792.006   341.8  1794.3   345.1 1794.35  372.91 1792.25
   384.2 1790.86   397.3 1790.73   416.8  1793.8  436.891793.787  473.551794.331
   511.4 1796.38  535.571799.178   560.3 1803.01  583.511807.952  585.461808.342
   654.8    1821   674.4 1825.91   684.2 1829.14   703.7 1836.94     733 1850.98
#Mann= 12 ,-1 , 0
       0     .06       0    5.03     .08       0   33.86     .12       0
   306.5    .045       0   321.5     .12       0   334.8    .016       0
  372.91     .12       0  436.89     .08       0  473.55     .12       0
  535.57     .06       0  583.51     .08       0  585.46     .12       0
Bank Sta=306.5,321.5
XS Rating Curve= 0 ,0
Exp/Cntr=0.3,0.1

Type RM Length L Ch R = 1 ,19774.9 ,402.5,403.6,403.3
XS GIS Cut Line= 2
     2031668.393      283619.988     2032068.461      284084.743
#Sta/Elev= 30
       0  1789.9      23 1789.35   52.141787.183    85.3 1783.47   131.2 1781.86
     141 1780.25   180.4 1782.99     223 1783.28   232.8 1782.16   259.1 1782.07
   268.9 1780.96   287.3 1777.29   302.3  1777.4   311.5 1779.92   327.9  1779.5
  336.791781.345  341.551782.142  380.531783.631   390.2 1783.44   409.9  1776.4
   416.5 1775.39   426.3  1777.6   439.4 1781.97   452.5 1783.63   465.7  1787.2
   501.7 1801.93   544.4 1814.99   593.6 1835.15   600.1 1838.58   613.2 1847.11
#Mann= 7 ,-1 , 0
       0     .06       0   52.14     .12       0   287.3    .045       0
   302.3    .016       0  336.79     .12       0  341.55     .08       0
  380.53     .12       0
#XS Ineff= 2 , 0
          216.76 1790.08
Permanent Ineff=
       F       F
Bank Sta=287.3,302.3
XS Rating Curve= 0 ,0
Exp/Cntr=0.3,0.1

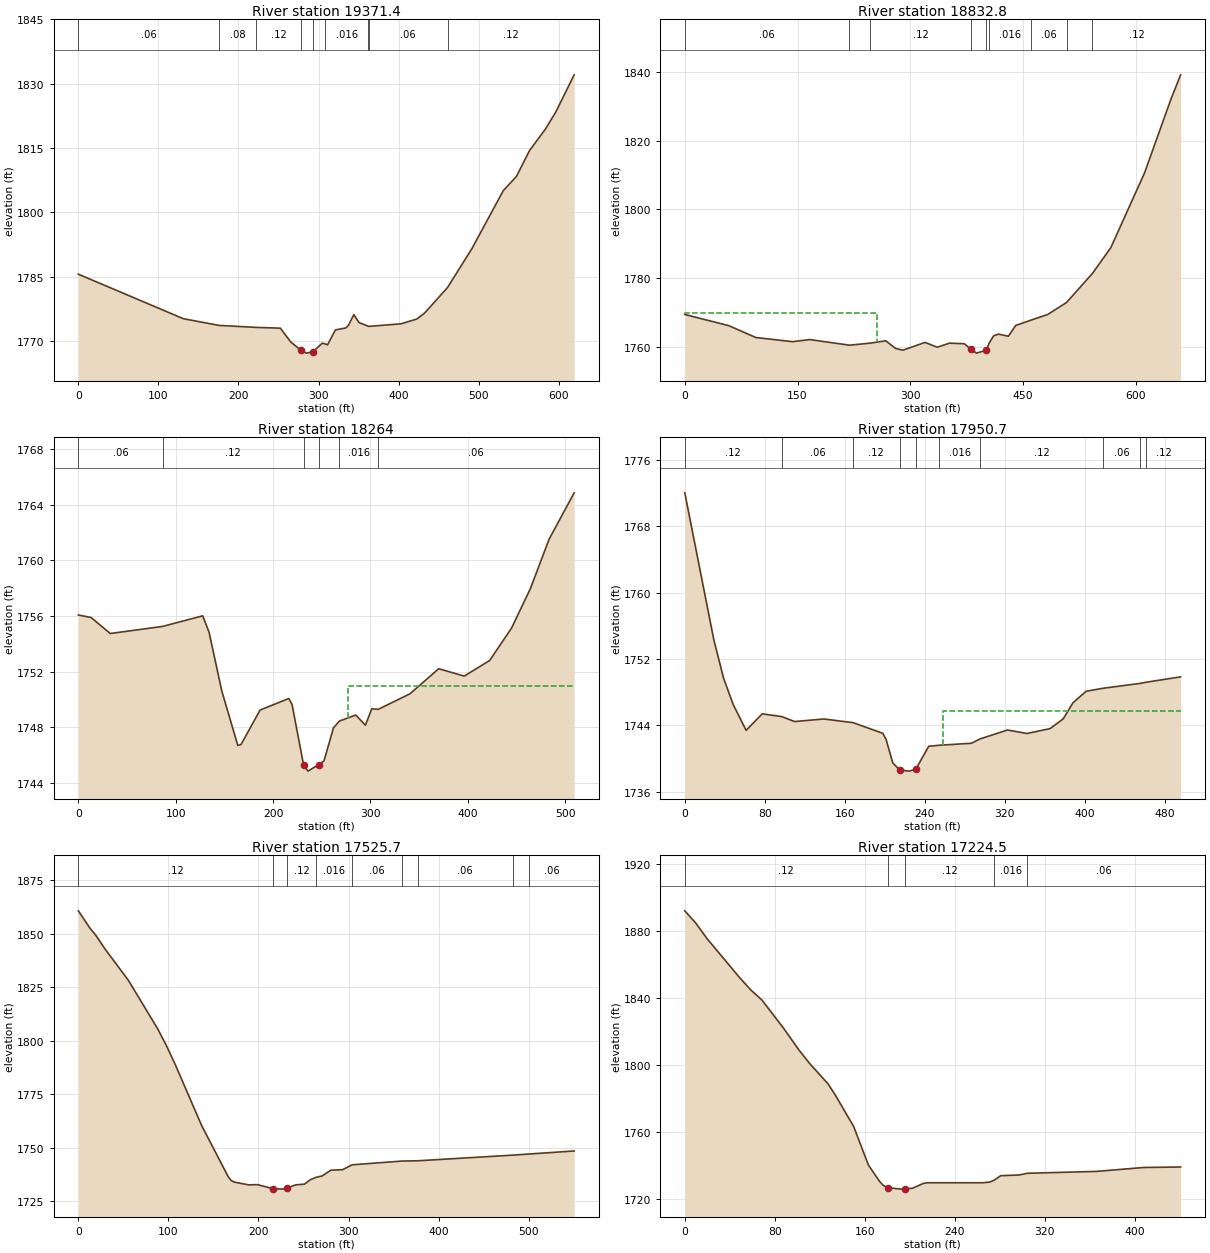
Type RM Length L Ch R = 1 ,19371.4 ,539.5,538.6,534.9
XS GIS Cut Line= 2
     2031333.705      283775.108     2031726.066      284254.275
#Sta/Elev= 30
       0 1785.61   131.1 1775.23  175.741773.663  222.361773.199   252.3 1773.02
   265.4 1769.79   277.9 1767.89   285.1  1767.2   292.9 1767.52   304.7 1769.52
  308.431769.357   311.3 1769.14   321.1 1772.61   334.2 1773.08   337.5 1773.71
   344.1 1776.18   350.6 1774.32  362.231773.474  363.131773.441     403 1774.03
   422.7 1775.15   432.5 1776.54  461.121782.495   491.5 1791.54   530.8 1805.09
   547.2 1808.39   563.6 1814.45   583.3 1819.41   596.4 1823.43   619.3 1832.09
#Mann= 9 ,-1 , 0
       0     .06       0  175.74     .08       0  222.36     .12       0
   277.9    .045       0   292.9     .12       0  308.43    .016       0
  362.23     .12       0  363.13     .06       0  461.12     .12       0
Bank Sta=277.9,292.9
XS Rating Curve= 0 ,0
Exp/Cntr=0.3,0.1

Type RM Length L Ch R = 1 ,18832.8 ,569.1,568.8,565.6
XS GIS Cut Line= 3
     2030864.955      284042.469     2031222.594      284431.358
      2031349.33       284466.08
#Sta/Elev= 30
       0 1769.38    58.7  1766.1    94.6 1762.66   143.5 1761.45   166.3 1762.07
   219.11760.434  246.05 1761.01   267.4 1761.71   280.5 1759.47   290.3 1758.98
   319.6 1761.24   335.9 1759.83   352.2 1761.03   371.8 1760.85   380.9 1759.23
   388.1 1758.12   401.1 1758.97  404.91 1760.99   410.9 1763.16   417.4 1763.65
   430.5 1763.04   440.3 1766.18  460.561767.724   482.7 1769.35  507.861772.855
  542.431781.338   566.8 1788.82   611.7 1810.59   646.9  1832.1   659.7 1839.15
#Mann= 9 ,-1 , 0
       0     .06       0   219.1     .08       0  246.05     .12       0
   380.9    .045       0   401.1     .12       0  404.91    .016       0
  460.56     .06       0  507.86     .08       0  542.43     .12       0
#XS Ineff= 2 , 0
          255.54 1769.81
Permanent Ineff=
       F       F
Bank Sta=380.9,401.1
XS Rating Curve= 0 ,0
Exp/Cntr=0.3,0.1

Type RM Length L Ch R = 1 ,18264   ,299.5,313.3,326.7
XS GIS Cut Line= 3
     2030522.565      284451.931      2030840.49      284720.341
     2030931.636      284739.872
#Sta/Elev= 30
       0 1756.08    13.1  1755.9    32.8 1754.75   86.54 1755.26   127.8 1756.02
   134.3 1754.84   147.4 1750.61   163.8 1746.71   167.1 1746.77   186.7 1749.25
   216.2 1750.08   219.5 1749.66  231.34 1745.32   235.9 1744.86   246.7 1745.32
   252.3 1745.59   262.1 1747.97  268.241748.461     285 1748.89   294.9 1748.16
   301.4 1749.34  308.061749.299   340.7 1750.42   370.2 1752.22   396.4 1751.69
   422.5 1752.81     445 1755.14   464.3 1757.97   483.6 1761.53   509.3 1764.86
#Mann= 6 ,-1 , 0
       0     .06       0   86.54     .12       0  231.34    .045       0
   246.7     .12       0  268.24    .016       0  308.06     .06       0
#XS Ineff= 2 , 0
                          276.99         1750.99
Permanent Ineff=
       F       F
Bank Sta=231.34,246.7
XS Rating Curve= 0 ,0
Exp/Cntr=0.3,0.1

Type RM Length L Ch R = 1 ,17950.7 ,447.5,425,396.9
XS GIS Cut Line= 4
     2030312.871        284582.4     2030406.245      284656.792
     2030494.787      284944.987      2030569.44      284939.778
#Sta/Elev= 30
       0 1772.06      29 1754.35    38.7 1749.73    48.4 1746.52    61.3 1743.41
    77.4  1745.4   96.961745.068   109.7 1744.47     139 1744.78  168.291744.335
     198 1743.05   201.3 1742.29   207.9  1739.5   214.7 1738.63   224.2 1738.49
   230.8 1738.69   243.9 1741.49  254.611741.613   286.5 1741.85  295.481742.385
   322.6 1743.45   342.2 1743.03   365.2 1743.62   378.3 1744.79   388.1 1746.74
   401.2 1748.12  417.931748.481  455.531749.076  461.291749.216   495.7 1749.86
#Mann= 10 ,-1 , 0
       0     .12       0   96.96     .06       0  168.29     .12       0
   214.7    .045       0   230.8     .12       0  254.61    .016       0
  295.48     .12       0  417.93     .06       0  455.53     .08       0
  461.29     .12       0
#XS Ineff= 2 , 0
                          258.52          1745.7
Permanent Ineff=
       F       F
Bank Sta=214.7,230.8
XS Rating Curve= 0 ,0
Exp/Cntr=0.3,0.1

Type RM Length L Ch R = 1 ,17525.7 ,303.5,301.3,298.6
XS GIS Cut Line= 3
     2029999.436      284914.845     2030375.734      285043.711
       2030523.5      285004.903
#Sta/Elev= 30
       0 1860.77      13  1852.6    19.6 1849.21    29.3 1843.12    55.4 1828.36
      88 1805.66    97.8 1797.71   107.6 1788.87   136.9 1760.34   166.3 1736.46
   169.5 1734.68   172.8  1733.9   189.1 1732.57   198.9 1732.68   216.4 1730.78
   228.2 1730.58   231.4 1731.01   241.3 1732.58     251  1732.9   257.6 1734.98
  264.091736.109   270.6 1736.74   280.4 1739.45   293.4 1739.68  303.981741.951
  359.751743.726   376.71743.837  482.131746.474  500.42    1747   550.5 1748.43
#Mann= 9 ,-1 , 0
       0     .12       0   216.4    .045       0   231.4     .12       0
  264.09    .016       0  303.98     .06       0  359.75     .08       0
   376.7     .06       0  482.13     .08       0  500.42     .06       0
Bank Sta=216.4,231.4
XS Rating Curve= 0 ,0
Exp/Cntr=0.3,0.1

Type RM Length L Ch R = 1 ,17224.5 ,453.4,457,458.6
XS GIS Cut Line= 2
     2029897.941      285214.344     2030330.233       285301.15
#Sta/Elev= 30
       0 1891.92     9.8 1884.57    19.6 1875.48      49 1851.85    58.8 1844.62
    68.6 1838.67    88.2 1821.52   101.2 1809.12     111 1800.81   127.4 1788.62
   133.9 1781.88   150.2 1763.15   163.3 1740.14   173.1 1730.49   176.4 1728.08
   180.5 1726.63   192.7  1725.8   195.5 1725.94   202.5 1726.34   212.3 1729.24
   215.6  1729.6   264.6 1729.59   271.1 1729.97  275.051731.111   280.9 1733.81
   297.2 1734.24  304.44 1735.25   365.8 1736.37   408.3 1738.73   440.9    1739
#Mann= 5 ,-1 , 0
       0     .12       0   180.5    .045       0   195.5     .12       0
  275.05    .016       0  304.44     .06       0
Bank Sta=180.5,195.5
XS Rating Curve= 0 ,0
Exp/Cntr=0.3,0.1

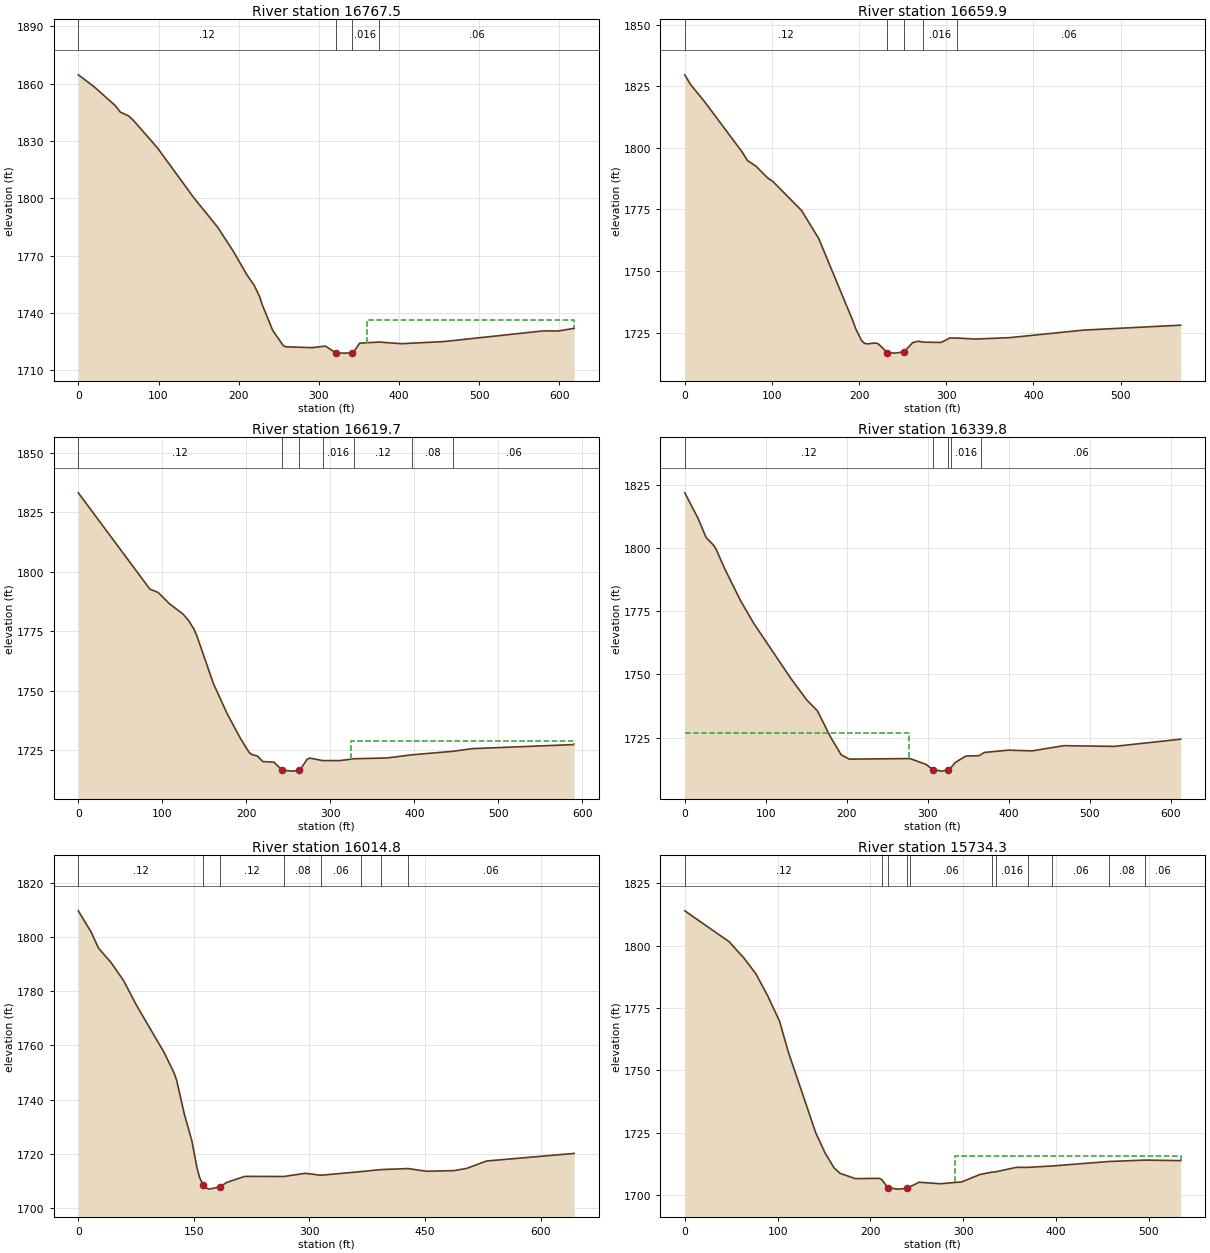
Type RM Length L Ch R = 1 ,16767.5 ,107.3,107.6,107.7
XS GIS Cut Line= 3
      2029755.58      285584.136     2030260.788       285747.33
     2030347.594      285736.914
#Sta/Elev= 30
       0 1864.59    19.7 1858.35    45.9 1848.55    52.4 1845.07    62.3 1843.19
    68.8  1840.7    98.3 1826.54   144.2 1800.16   173.7 1784.87   193.4 1772.15
   209.7 1760.25   219.6  1754.2   226.1 1748.46   229.4 1744.21   242.5 1730.74
   255.6 1722.86   258.9 1722.24   291.7 1721.78   308.1 1722.63   321.2 1719.02
     331 1718.93   340.8 1719.06   344.1 1719.96   350.7 1724.14  375.06 1724.72
   403.1 1723.87   455.5 1724.97   579.5 1730.55   598.9 1730.53   618.3 1731.91
#Mann= 4 ,-1 , 0
       0     .12       0   321.2    .045       0   340.8    .016       0
  375.06     .06       0
#XS Ineff= 2 , 0
                          359.94         1736.46
Permanent Ineff=
       F       F
Bank Sta=321.2,340.8
XS Rating Curve= 0 ,0
Exp/Cntr=0.3,0.1

Type RM Length L Ch R = 1 ,16659.9 ,40,40.2,40.3
XS GIS Cut Line= 2
     2029793.774      285705.664     2030333.705      285884.483
#Sta/Elev= 30
       0 1829.62     6.5 1825.74    22.9 1818.64    65.4  1798.5    71.9 1794.86
    81.7 1792.55    94.8 1787.89   101.3 1786.27     134 1774.57   153.6 1763.24
   192.9 1729.76   196.1 1726.61   202.7 1721.87   205.9 1720.77   209.2 1720.47
     219 1720.85   222.3 1720.39   232.3 1716.97   241.9 1716.73   251.7 1717.35
   261.5    1721     268 1721.56  273.421721.183   294.2 1721.06     304 1722.87
  312.791722.837   333.4 1722.43   372.6 1723.01   457.6 1726.07   568.8 1728.07
#Mann= 5 ,-1 , 0
       0     .12       0   232.3    .045       0   251.7     .12       0
  273.42    .016       0  312.79     .06       0
Bank Sta=232.3,251.7
XS Rating Curve= 0 ,0
Exp/Cntr=0.3,0.1

Type RM Length L Ch R = 1 ,16619.7 ,279.7,279.9,279.8
XS GIS Cut Line= 2
     2029768.601      285737.782     2030327.628      285927.018
#Sta/Elev= 30
       0  1833.1    85.2 1792.63    95.1 1791.23   108.2 1786.59   124.6 1782.15
   131.2 1779.49   137.7 1775.77     141 1773.11   160.7 1753.04   177.1 1740.33
   193.4 1729.66   203.3 1724.06   206.6 1723.14   213.1 1722.54   219.7 1720.19
   232.8 1719.96   242.7 1716.54   255.8 1716.18   262.3  1716.5   265.6 1717.56
   272.1 1721.06   275.4 1721.66  290.841720.607   311.5 1720.61  327.691721.372
   367.2  1721.7  397.741723.052  446.181724.516   468.9 1725.63   590.2 1727.34
#Mann= 7 ,-1 , 0
       0     .12       0   242.7    .045       0   262.3     .12       0
  290.84    .016       0  327.69     .12       0  397.74     .08       0
  446.18     .06       0
#XS Ineff= 2 , 0
                          324.72         1728.89
Permanent Ineff=
       F       F
Bank Sta=242.7,262.3
XS Rating Curve= 0 ,0
Exp/Cntr=0.3,0.1

Type RM Length L Ch R = 1 ,16339.8 ,318.5,324.9,328.2
XS GIS Cut Line= 2
     2029649.677       285988.65     2030231.274      286179.622
#Sta/Elev= 30
       0 1821.72    16.4 1811.61    26.2 1804.14      36 1800.85    39.3 1798.99
    49.1 1791.85    68.7  1779.2    85.1 1770.17   130.9 1748.41   150.6 1739.89
   163.7 1735.62     180 1725.21   193.1 1718.22     203 1716.51   278.2 1716.73
   297.9 1714.41   306.4 1712.35   317.5 1711.77  325.35 1712.27  328.571713.115
   333.9 1715.17     347 1717.73   363.4 1717.86  366.251718.466   369.9 1719.15
   399.4 1720.05   428.8 1719.77   468.1 1721.83   530.3 1721.54   612.2 1724.38
#Mann= 5 ,-1 , 0
       0     .12       0   306.4    .045       0  325.35     .12       0
  328.57    .016       0  366.25     .06       0
#XS Ineff= 2 , 0
          276.42 1726.75
Permanent Ineff=
       F       F
Bank Sta=306.4,325.35
XS Rating Curve= 0 ,0
Exp/Cntr=0.3,0.1

Type RM Length L Ch R = 1 ,16014.8 ,286.7,280.5,274.5
XS GIS Cut Line= 3
     2029547.246      286150.108     2029929.191      286391.428
     2030116.691      286351.497
#Sta/Elev= 30
       0 1809.64    16.4 1801.91    26.2 1795.89    42.6 1790.51    58.9 1783.84
    75.3  1774.9   111.3 1757.42   124.4 1749.78   127.7 1747.03   137.5 1734.78
   147.3 1724.84   153.9 1715.02   157.2 1711.45  162.02 1708.42   163.7 1707.62
   170.2    1707   183.3 1707.81   193.2 1709.54   216.1  1711.7   266.81711.661
   294.6 1712.84  314.651712.117  366.391713.447  393.011714.208  427.951714.584
   451.8 1713.59   487.5 1713.82   503.8 1714.63   529.8 1717.37   643.5 1720.17
#Mann= 8 ,-1 , 0
       0     .12       0  162.02    .045       0   183.3     .12       0
   266.8     .08       0  314.65     .06       0  366.39    .016       0
  393.01     .08       0  427.95     .06       0
Bank Sta=162.02,183.3
XS Rating Curve= 0 ,0
Exp/Cntr=0.3,0.1

Type RM Length L Ch R = 1 ,15734.3 ,214.7,218.8,222
XS GIS Cut Line= 3
     2029468.961      286399.708     2029542.659      286479.166
     2029953.801      286590.265
#Sta/Elev= 30
       0 1813.89    47.8 1801.52    63.8 1794.97    76.5 1788.74    89.2 1779.99
     102 1769.82   111.6 1757.37   141.1 1725.06     151 1717.12   160.8 1711.07
   167.3 1708.84   183.7 1706.73   209.9 1706.83  212.511706.205  218.91 1703.07
   229.6 1702.52   239.4 1702.81  243.111703.547   252.5 1705.28   275.4 1704.67
   298.4 1705.41     318 1708.37  330.821709.293   334.91709.448   357.4 1711.24
  369.39 1711.22  396.091711.793  457.29 1713.58   496.1 1714.14   534.3 1713.92
#Mann= 11 ,-1 , 0
       0     .12       0  212.51     .08       0  218.91    .045       0
   239.4     .08       0  243.11     .06       0  330.82     .08       0
   334.9    .016       0  369.39     .08       0  396.09     .06       0
  457.29     .08       0   496.1     .06       0
#XS Ineff= 2 , 0
                          291.48         1715.75
Permanent Ineff=
       F       F
Bank Sta=218.91,239.4
XS Rating Curve= 0 ,0
Exp/Cntr=0.3,0.1

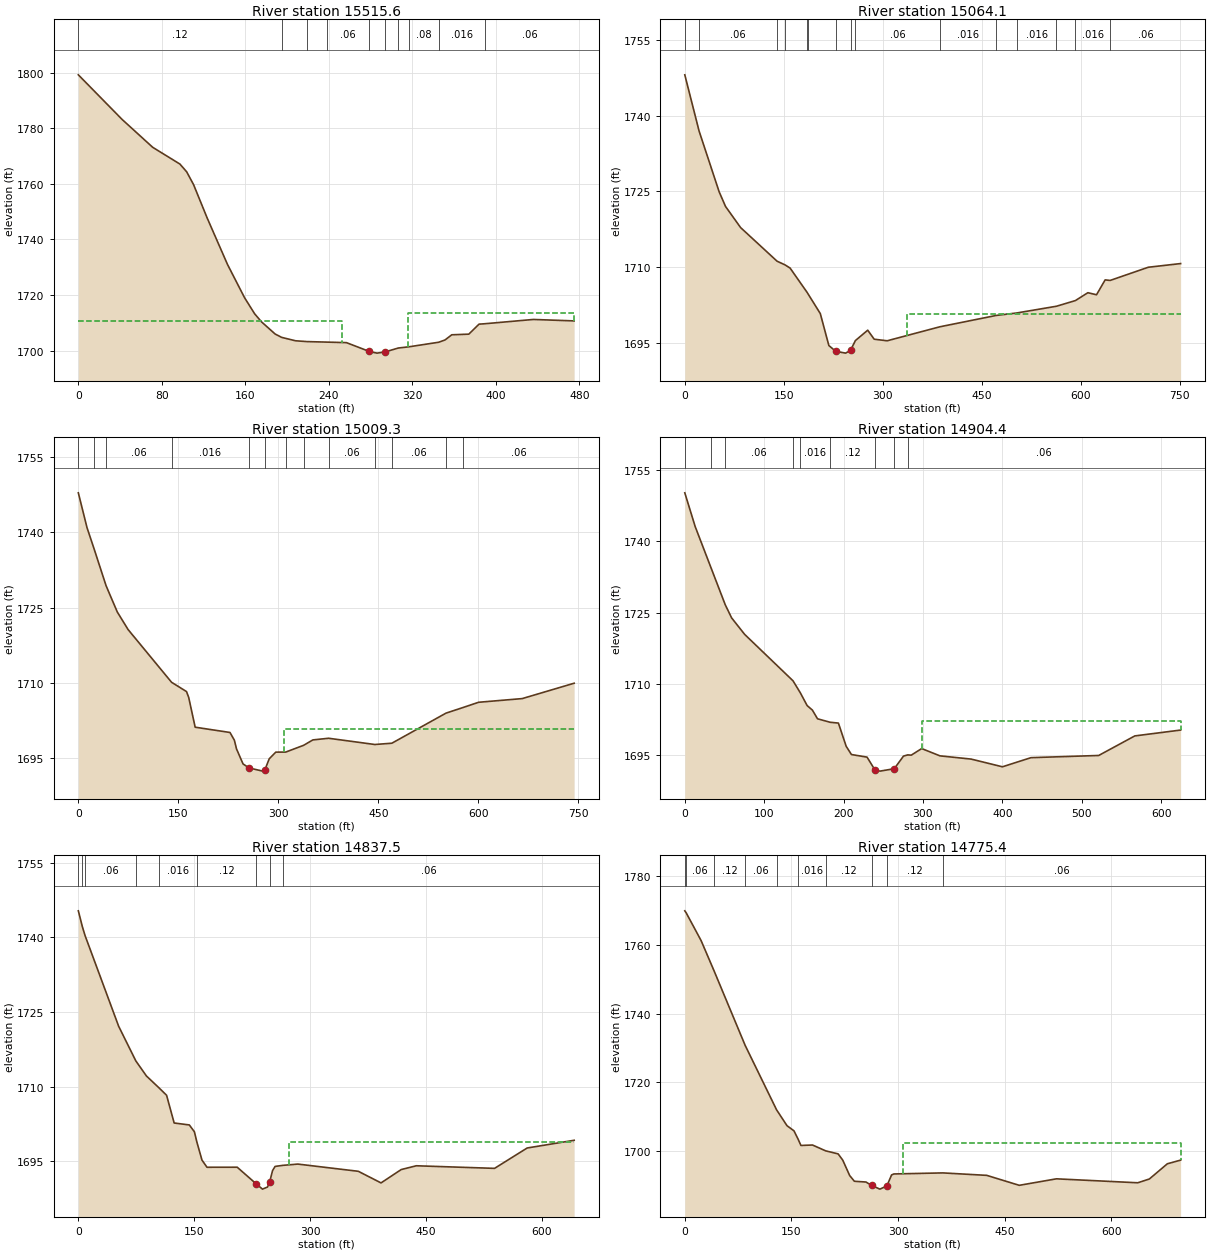
Type RM Length L Ch R = 1 ,15515.6 ,483,451.5,418.5
XS GIS Cut Line= 3
     2029359.023      286549.935     2029391.864      286613.216
     2029756.158      286786.914
#Sta/Elev= 30
       0 1799.18    42.1 1783.08    71.3 1773.11    97.3 1767.11   103.8 1764.31
   110.4  1759.7   123.4 1747.73   142.9 1731.01   159.2 1719.09   168.9 1713.28
   175.4 1710.42   188.5 1706.03  194.741704.821     208  1703.6  218.831703.307
   237.81703.121   256.8 1702.93   278.8 1699.75   286.1 1699.16   293.8 1699.59
  306.441700.991     317 1701.45  345.18 1703.07   351.2 1703.89   357.7 1705.75
     374 1705.98   383.8 1709.58  389.121709.714   435.8 1711.26   474.9 1710.74
#Mann= 10 ,-1 , 0
       0     .12       0  194.74     .06       0  218.83     .12       0
   237.8     .06       0   278.8    .045       0   293.8     .08       0
  306.44     .06       0     317     .08       0  345.18    .016       0
  389.12     .06       0
#XS Ineff= 2 , 0
          252.13 1710.73  316.05         1713.63
Permanent Ineff=
       F       F
Bank Sta=278.8,293.8
XS Rating Curve= 0 ,0
Exp/Cntr=0.3,0.1

Type RM Length L Ch R = 1 ,15064.1 ,55,54.8,55
XS GIS Cut Line= 4
     2029207.981      287160.612     2029357.721       287159.31
     2029609.023       286784.31     2029757.461      286809.049
#Sta/Elev= 30
       0 1748.14   21.671736.985    52.1 1724.92    61.8 1722.01    84.6 1717.83
  139.821711.166  151.951710.426   159.6  1709.8  184.991705.053  187.511704.531
   205.4 1700.77   218.4 1694.42   228.8 1693.28   243.8 1692.92   251.2 1693.47
  258.621695.412   277.3 1697.47   287.1 1695.68   306.8 1695.37   386.61698.145
  471.961700.396  503.351700.889  563.441702.224  592.111703.348     611 1704.91
   624.1  1704.5   637.2 1707.45  644.771707.343   702.6 1709.96   751.6 1710.69
#Mann= 15 ,-1 , 0
       0     .08       0   21.67     .06       0  139.82     .12       0
  151.95     .08       0  184.99    .016       0  187.51     .08       0
   228.8    .045       0   251.2     .12       0  258.62     .06       0
   386.6    .016       0  471.96     .08       0  503.35    .016       0
  563.44     .06       0  592.11    .016       0  644.77     .06       0
#XS Ineff= 2 , 0
                          336.36          1700.7
Permanent Ineff=
       F       F
Bank Sta=228.8,251.2
XS Rating Curve= 0 ,0
Exp/Cntr=0.3,0.1

Type RM Length L Ch R = 1 ,15009.3 ,79.8,104.9,129.5
XS GIS Cut Line= 4
     2029207.981      287193.164     2029399.388       287190.56
      2029650.69       286815.56     2029749.648      286833.789
#Sta/Elev= 30
       0 1747.84      13 1740.92   23.311736.826   41.571729.372    58.4 1724.14
    74.6 1720.64  139.831710.144   162.2  1708.3   165.5 1707.14   175.2 1701.21
   227.4 1700.16     234 1698.62   237.2 1696.89     247  1693.9   256.1  1693.1
   276.5 1692.47   279.7 1692.73   286.3 1694.93   296.1 1696.25     311 1696.26
  337.911697.611   351.7 1698.68  375.331699.009  444.581697.768  470.181698.025
  551.251704.003   576.31705.102   600.3 1706.17   665.6  1706.9   743.5 1709.96
#Mann= 13 ,-1 , 0
       0     .06       0   23.31     .08       0   41.57     .06       0
  139.83    .016       0   256.1    .045       0   279.7    .016       0
     311     .08       0  337.91    .016       0  375.33     .06       0
  444.58     .08       0  470.18     .06       0  551.25     .08       0
   576.3     .06       0
#XS Ineff= 2 , 0
                          307.95         1700.78
Permanent Ineff=
       F       F
Bank Sta=256.1,279.7
XS Rating Curve= 0 ,0
Exp/Cntr=0.3,0.1

Type RM Length L Ch R = 1 ,14904.4 ,66.3,66.9,67.1
XS GIS Cut Line= 3
     2029202.773      287204.882     2029751.661       287252.04
     2029801.911      287198.154
#Sta/Elev= 30
       0 1750.19    13.1 1743.09   32.791734.544   50.961726.665      59  1723.9
    75.4 1720.44  136.34 1710.68  145.561708.155   154.1 1705.48   160.7 1704.53
   167.2  1702.7  183.121701.968   193.5  1701.8   203.3 1696.92   209.9 1695.19
   229.6 1694.64   239.4 1691.98   245.9  1691.7   263.9 1692.21   275.5 1694.86
   280.81695.108   285.3 1695.06   298.4 1696.44   321.4 1694.91   360.7 1694.23
   400.1 1692.61   436.1 1694.53   521.4 1694.99   566.9  1699.1   624.6 1700.33
#Mann= 9 ,-1 , 0
       0     .06       0   32.79     .08       0   50.96     .06       0
  136.34     .12       0  145.56    .016       0  183.12     .12       0
   239.4    .045       0   263.9     .12       0   280.8     .06       0
#XS Ineff= 2 , 0
                          299.29         1702.31
Permanent Ineff=
       F       F
Bank Sta=239.4,263.9
XS Rating Curve= 0 ,0
Exp/Cntr=0.3,0.1

Type RM Length L Ch R = 1 ,14837.5 ,62.6,62.1,63
XS GIS Cut Line= 3
     2029214.678      287268.497     2029779.596      287327.278
     2029831.679      287275.195
#Sta/Elev= 30
       0 1745.34    5.26 1742.13    8.76 1740.35    52.2 1722.15   74.451715.189
    88.1 1712.18  104.141709.824   114.2  1708.3     124 1702.73   143.6 1702.34
   150.2 1700.97  153.371698.919     160 1695.28   166.5 1693.84   205.6 1693.85
   230.1 1690.52   238.3 1689.45   244.8 1689.87  247.59 1690.88   251.3 1693.16
   254.6 1694.01  264.471694.221     284 1694.48   362.3 1693.03   391.7  1690.7
   417.8 1693.38   437.4 1694.14   538.6 1693.62   580.8 1697.71   641.6 1699.26
#Mann= 9 ,-1 , 0
       0     .06       0    5.26     .12       0    8.76     .06       0
   74.45     .12       0  104.14    .016       0  153.37     .12       0
   230.1    .045       0  247.59     .12       0  264.47     .06       0
#XS Ineff= 2 , 0
                          272.44         1698.99
Permanent Ineff=
       F       F
Bank Sta=230.1,247.59
XS Rating Curve= 0 ,0
Exp/Cntr=0.3,0.1

Type RM Length L Ch R = 1 ,14775.4 ,81,83.2,84.3
XS GIS Cut Line= 3
     2029162.408      287292.122     2029808.242      287428.841
     2029843.398       287415.82
#Sta/Elev= 30
       0 1769.99    2.071769.363    22.9 1761.34   41.081752.554   84.911730.805
  129.111712.034   143.8  1707.4   153.6  1705.9  159.311703.527   163.4 1701.64
   179.7 1701.77  198.181700.071   215.7 1699.19   222.2 1697.38     232 1692.87
   238.6 1691.21   254.9 1690.99     263 1689.98   274.5 1688.92   284.3 1689.85
   290.9 1693.04   294.1 1693.34  363.121693.644   424.8 1692.93   470.6 1690.03
   522.9 1691.92   637.3 1690.77   653.6 1691.87   678.9  1696.3   697.6 1697.37
#Mann= 10 ,-1 , 0
       0    .016       0    2.07     .06       0   41.08     .12       0
   84.91     .06       0  129.11     .12       0  159.31    .016       0
  198.18     .12       0     263    .045       0   284.3     .12       0
  363.12     .06       0
#XS Ineff= 2 , 0
                          307.24         1702.29
Permanent Ineff=
       F       F
Bank Sta=263,284.3
XS Rating Curve= 0 ,0
Exp/Cntr=0.3,0.1

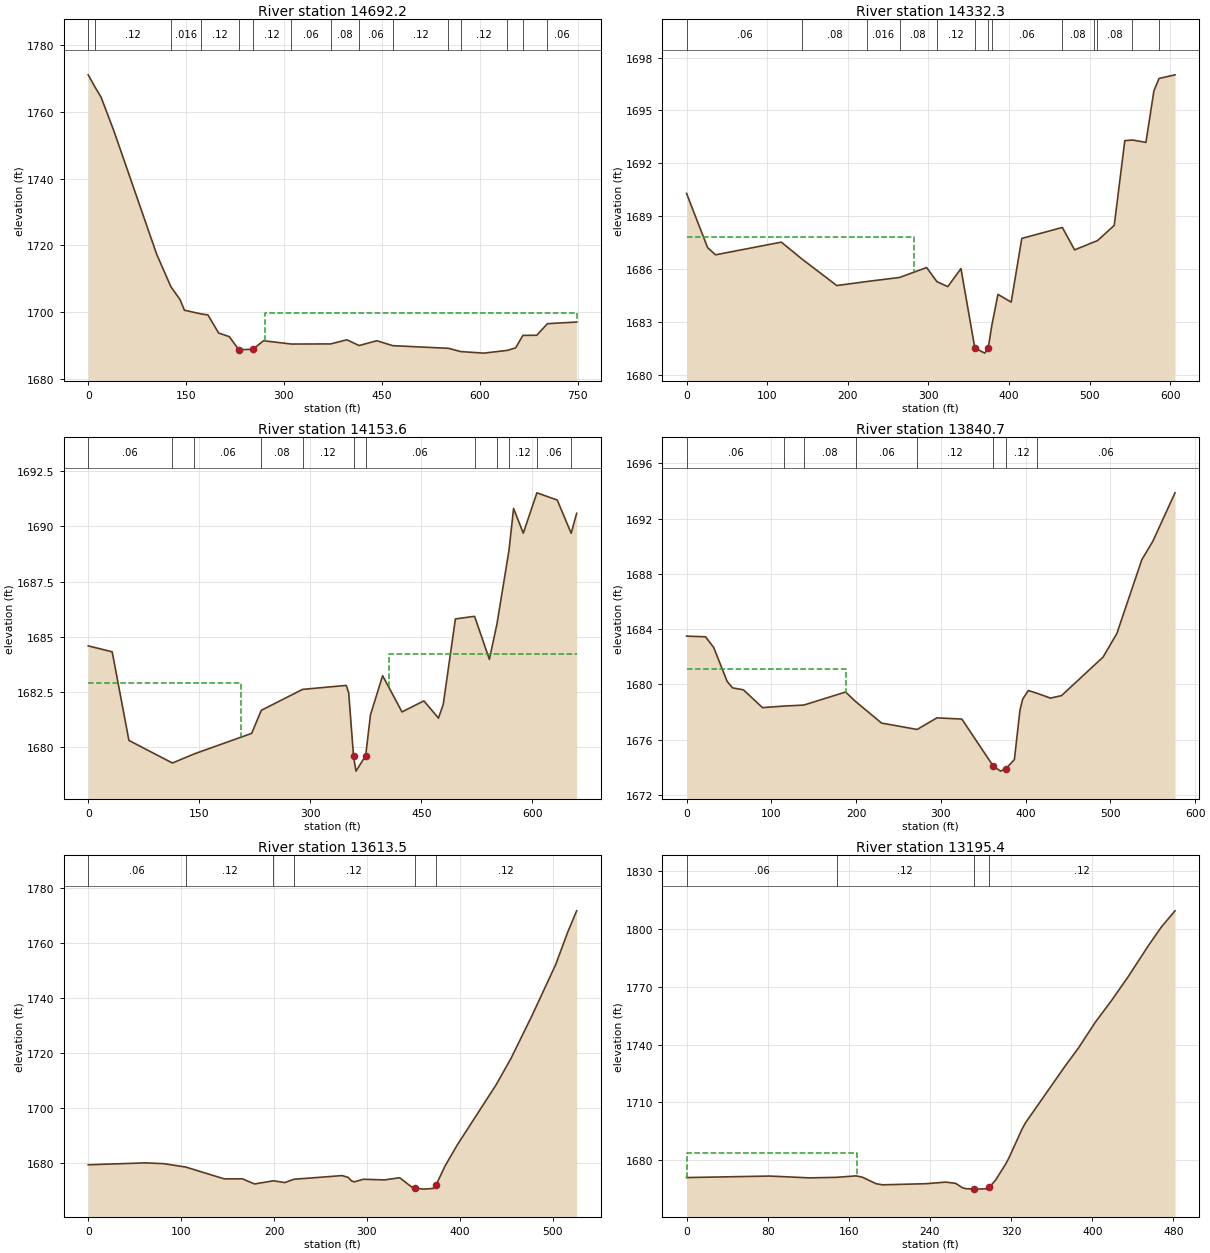
Type RM Length L Ch R = 1 ,14692.2 ,381.3,360,336.5
XS GIS Cut Line= 3
     2029160.094      287374.067     2029793.919      287496.549
      2029869.44      287426.237
#Sta/Elev= 30
       0 1771.15   10.67  1767.4    19.7 1764.45    39.3 1754.36   104.9 1717.34
  126.691707.594   140.9 1703.67   147.5 1700.52  173.121699.411   183.5 1699.12
   199.9 1693.69   216.3 1692.59   230.8 1688.68   252.3  1688.8   268.7 1691.37
  311.511690.376  371.681690.417   396.5 1691.65  415.281689.926   442.4 1691.37
  466.921689.887  552.181689.094  570.981688.117   606.2 1687.65  642.431688.469
   655.2 1689.25  666.311692.977   687.5 1693.01  703.911696.488   748.7 1696.98
#Mann= 15 ,-1 , 0
       0    .016       0   10.67     .12       0  126.69    .016       0
  173.12     .12       0   230.8    .045       0   252.3     .12       0
  311.51     .06       0  371.68     .08       0  415.28     .06       0
  466.92     .12       0  552.18     .08       0  570.98     .12       0
  642.43     .08       0  666.31    .016       0  703.91     .06       0
#XS Ineff= 2 , 0
                          271.59         1699.62
Permanent Ineff=
       F       F
Bank Sta=230.8,252.3
XS Rating Curve= 0 ,0
Exp/Cntr=0.3,0.1

Type RM Length L Ch R = 1 ,14332.3 ,177.3,178.6,179.5
XS GIS Cut Line= 3
     2029395.481      287789.518     2029486.627      287796.028
     2029864.521      287446.549
#Sta/Elev= 30
       0  1690.3    26.1 1687.23    35.9 1686.82   117.6 1687.54  143.611686.568
   186.4 1685.08  224.13 1685.31  264.371685.538   297.9  1686.1  310.721685.298
   324.2 1685.02   340.5 1686.04   357.7 1681.54     370 1681.25  374.27 1681.53
   378.81682.823   386.4 1684.58   402.8 1684.14     416 1687.75  466.291688.372
   481.5  1687.1  505.771687.552  509.79 1687.62   530.7 1688.49   543.8 1693.29
   553.31693.327     570 1693.19   579.9 1696.11  586.291696.813   606.1 1697.02
#Mann= 13 ,-1 , 0
       0     .06       0  143.61     .08       0  224.13    .016       0
  264.37     .08       0  310.72     .12       0   357.7    .045       0
  374.27     .12       0   378.8     .06       0  466.29     .08       0
  505.77     .12       0  509.79     .08       0   553.3    .016       0
  586.29     .06       0
#XS Ineff= 2 , 0
          282.39 1687.84
Permanent Ineff=
       F       F
Bank Sta=357.7,374.27
XS Rating Curve= 0 ,0
Exp/Cntr=0.3,0.1

Type RM Length L Ch R = 1 ,14153.6 ,285.8,312.9,340.4
XS GIS Cut Line= 3
     2029447.565      287865.039     2029607.721      287888.476
     2029992.125      287571.983
#Sta/Elev= 30
       0 1684.59    32.4 1684.32      55 1680.31  113.731679.287  143.111679.699
   220.8 1680.63  233.831681.673  289.55 1682.62   348.6  1682.8   351.9 1682.46
   358.4 1679.59   361.7 1678.92   374.8 1679.62   381.3 1681.47   397.7 1683.24
   423.9  1681.6   453.4  1682.1   473.1 1681.32   479.6 1681.94     496 1685.81
   521.91685.927   541.9 1683.98  552.131685.579  568.371688.912   574.6 1690.81
   587.7 1689.69  606.111691.517   633.6 1691.19  652.381689.687   659.8 1690.59
#Mann= 12 ,-1 , 0
       0     .06       0  113.73    .016       0  143.11     .06       0
  233.83     .08       0  289.55     .12       0   358.4    .045       0
   374.8     .06       0   521.9     .12       0  552.13     .08       0
  568.37     .12       0  606.11     .06       0  652.38     .12       0
#XS Ineff= 2 , 0
          206.82 1682.89  405.68         1684.24
Permanent Ineff=
       F       F
Bank Sta=358.4,374.8
XS Rating Curve= 0 ,0
Exp/Cntr=0.3,0.1

Type RM Length L Ch R = 1 ,13840.7 ,224.8,227.2,229.7
XS GIS Cut Line= 3
     2029444.961      287905.403     2029527.779      287898.768
     2029959.573      288137.087
#Sta/Elev= 30
       0 1683.49    22.4 1683.44      32 1682.67    47.9 1680.21    54.3 1679.74
    67.1  1679.6    89.6 1678.31  115.271678.425  138.331678.495   187.6 1679.44
  199.461678.751   230.1 1677.19  272.071676.729   295.4 1677.57   324.8 1677.48
   361.8 1674.08   370.5 1673.71   376.8 1673.89   386.8 1674.55   393.4 1678.14
   396.6 1678.93   403.2 1679.55  413.861679.343   429.3    1679   442.4 1679.18
   491.4 1681.97   507.7 1683.68   537.1 1689.02   550.2 1690.37   576.3 1693.87
#Mann= 8 ,-1 , 0
       0     .06       0  115.27    .016       0  138.33     .08       0
  199.46     .06       0  272.07     .12       0   361.8    .045       0
   376.8     .12       0  413.86     .06       0
#XS Ineff= 2 , 0
          188.35 1681.08
Permanent Ineff=
       F       F
Bank Sta=361.8,376.8
XS Rating Curve= 0 ,0
Exp/Cntr=0.3,0.1

Type RM Length L Ch R = 1 ,13613.5 ,399.5,418.1,436.5
XS GIS Cut Line= 3
     2029368.572      288023.459     2029697.854      288256.879
     2029727.802      288375.369
#Sta/Elev= 30
       0 1679.22    61.8 1679.92    81.4 1679.62  105.031678.386   146.5 1674.09
     166 1674.11     179 1672.24  199.39  1673.4   211.6 1672.74  221.341673.943
   273.4 1675.29   279.9 1674.62   283.2 1673.41   286.4    1673   296.2 1673.95
     319 1673.72   335.3 1674.51   348.3  1671.1   351.5 1670.75   361.3 1670.36
   371.1  1670.6   374.3 1671.75   384.1 1678.78   397.1 1686.34     439 1708.28
   455.1 1717.94   477.6 1733.42   503.3 1752.16   516.2 1763.93   525.8 1771.66
#Mann= 6 ,-1 , 0
       0     .06       0  105.03     .12       0  199.39     .06       0
  221.34     .12       0   351.5    .045       0   374.3     .12       0
Bank Sta=351.5,374.3
XS Rating Curve= 0 ,0
Exp/Cntr=0.3,0.1

Type RM Length L Ch R = 1 ,13195.4 ,532.1,546.1,559
XS GIS Cut Line= 2
     2029247.044      288101.584     2029313.739      288578.494
#Sta/Elev= 30
       0 1671.11    81.9 1671.89   121.2 1670.95  147.861671.225   167.1 1671.99
   173.6 1671.26   186.7 1667.95   193.3 1667.35   235.9 1667.93   255.5 1668.75
   265.3 1668.12   271.9 1665.88   275.2 1665.36   283.5 1665.17     285 1665.12
   294.8 1665.28   298.5 1666.12   304.6 1669.72   314.5 1678.02   317.8 1681.21
   330.9 1696.37   334.1 1699.42   373.4 1728.96   386.6 1738.37   402.9 1751.48
   419.3 1763.02   435.7 1775.36   455.3  1791.2   468.4 1801.07   481.6 1809.27
#Mann= 4 ,-1 , 0
       0     .06       0  147.86     .12       0   283.5    .045       0
   298.5     .12       0
#XS Ineff= 2 , 0
          168.32 1683.85
Permanent Ineff=
       F       F
Bank Sta=283.5,298.5
XS Rating Curve= 0 ,0
Exp/Cntr=0.3,0.1