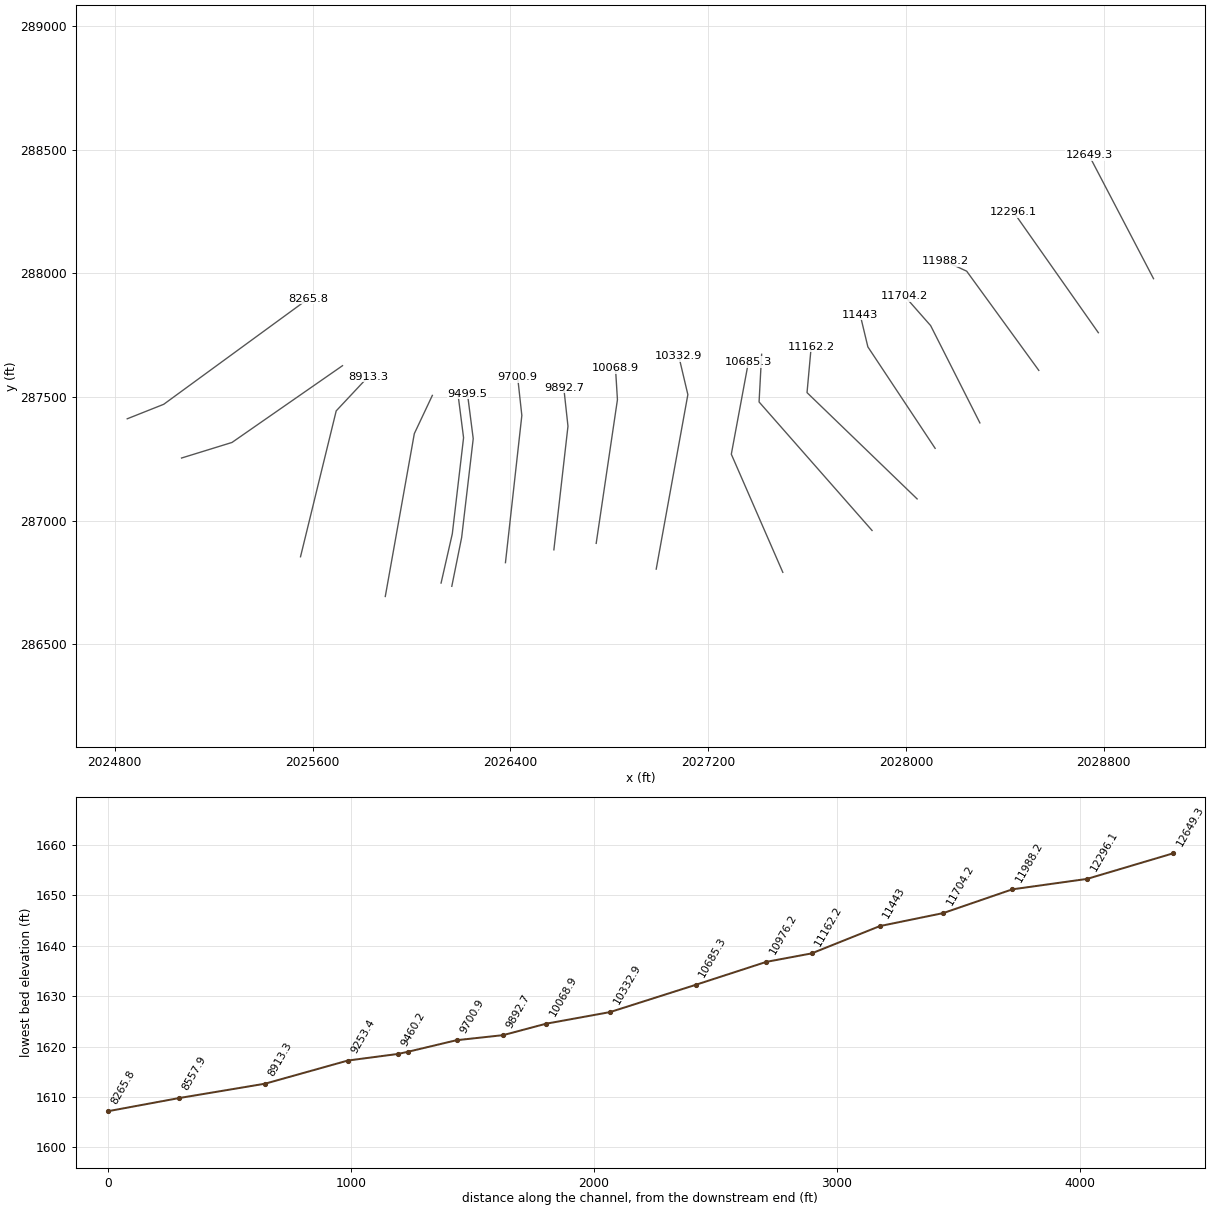
HEC-RAS study LICKCK1.prj: LICKCK1

--- LICKCK1.g01 (geometry) --- (continued)

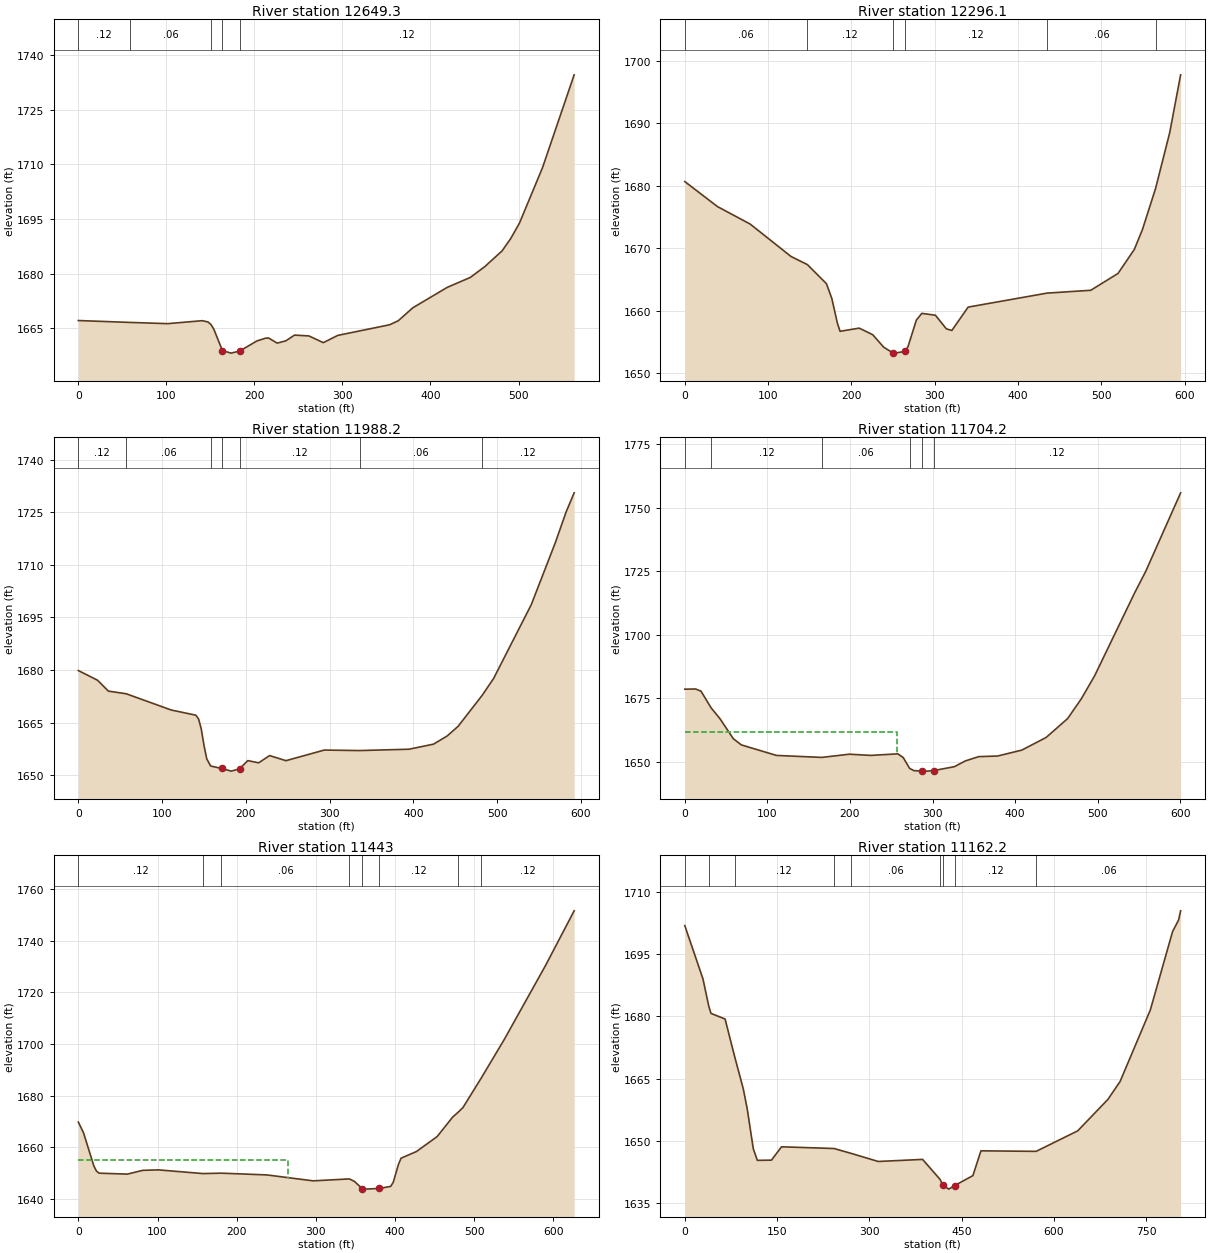
Type RM Length L Ch R = 1 ,12649.3 ,352.7,353.2,355.2
XS GIS Cut Line= 2
     2029001.818      287977.886     2028740.823      288476.931
#Sta/Elev= 30
       0 1667.18   58.271666.668   101.5 1666.33   140.8 1667.14   147.3 1666.79
   150.71666.081   153.9 1664.82   163.7 1658.93   173.5 1658.25   183.4 1658.84
     203 1661.61   212.8 1662.35   216.1  1662.4   225.9 1660.99   235.8 1661.63
   245.6 1663.19   261.9 1662.96   278.3 1661.12   294.7 1663.11   353.6 1666.02
   363.4 1667.12   379.8 1670.65   419.1 1676.28   445.3    1679   461.7 1681.96
   481.3 1686.26   491.1 1689.63     501 1693.84   527.2 1709.04   563.2 1734.52
#Mann= 5 ,-1 , 0
       0     .12       0   58.27     .06       0   150.7     .12       0
   163.7    .045       0   183.4     .12       0
Bank Sta=163.7,183.4
XS Rating Curve= 0 ,0
Exp/Cntr=0.3,0.1

Type RM Length L Ch R = 1 ,12296.1 ,305.1,307.9,309.1
XS GIS Cut Line= 2
     2028778.583      287759.483     2028436.135      288246.462
#Sta/Elev= 30
       0 1680.64    39.2 1676.64    78.5 1673.84   127.6 1668.65   147.2 1667.36
   170.1  1664.3   176.6 1661.91   183.2    1658   186.4 1656.69   209.4  1657.2
   225.7 1656.14   238.8 1654.15   249.9 1653.23   251.9  1653.2   264.9 1653.49
   268.2 1654.32     278 1658.48   284.6 1659.56   300.9 1659.26     314 1657.09
   320.6 1656.82   340.2 1660.56  434.99  1662.8   487.4 1663.25   520.1 1665.94
   539.7 1669.78   549.5 1672.98  565.251679.548   582.2 1688.46   595.3 1697.71
#Mann= 6 ,-1 , 0
       0     .06       0   147.2     .12       0   249.9    .045       0
   264.9     .12       0  434.99     .06       0  565.25     .12       0
Bank Sta=249.9,264.9
XS Rating Curve= 0 ,0
Exp/Cntr=0.3,0.1

Type RM Length L Ch R = 1 ,11988.2 ,287.4,284.1,280.6
XS GIS Cut Line= 3
     2028537.698      287607.139     2028246.031      288008.181
     2028158.792      288048.546
#Sta/Elev= 30
       0 1679.83    22.8 1677.09    35.9 1673.96   57.131673.208   110.9 1668.57
   140.3 1667.09   143.6    1666   146.8 1663.14   150.1 1658.39   153.3 1654.66
  157.951652.599   171.1 1651.88   182.7 1651.13   192.5 1651.79   202.3 1654.13
   215.3  1653.5   228.4 1655.57   247.9 1654.11   293.6 1657.14  335.771656.998
   394.8 1657.38   424.1 1658.83   440.4 1661.16   453.5 1663.93  482.281672.792
   495.9  1677.6   540.8 1698.63   569.6 1716.37   582.4 1725.07     592 1730.54
#Mann= 7 ,-1 , 0
       0     .12       0   57.13     .06       0  157.95     .12       0
   171.1    .045       0   192.5     .12       0  335.77     .06       0
  482.28     .12       0
Bank Sta=171.1,192.5
XS Rating Curve= 0 ,0
Exp/Cntr=0.3,0.1

Type RM Length L Ch R = 1 ,11704.2 ,258.8,261.2,263.7
XS GIS Cut Line= 3
     2028299.417        287394.9     2028100.198      287788.129
     2027994.729      287907.921
#Sta/Elev= 30
       0 1678.63    13.1  1678.7    19.6 1677.86   32.011671.229    42.4 1667.12
    58.8 1659.15    68.6 1656.72     111  1652.6  166.021651.821   199.2 1653.08
   225.3 1652.61     258 1653.22   264.5 1651.76   272.21647.519   277.6  1646.6
   286.7 1646.48   293.9 1646.43   301.7 1646.67   326.5 1648.18   339.6 1650.42
   355.9 1652.13   378.8 1652.36   408.2  1654.7   437.6 1659.67   463.6 1667.09
   479.9 1674.72   496.2 1683.84     545 1716.65   558.1 1724.89   600.4 1755.78
#Mann= 6 ,-1 , 0
       0    .016       0   32.01     .12       0  166.02     .06       0
   272.2     .12       0   286.7    .045       0   301.7     .12       0
#XS Ineff= 2 , 0
          257.53 1661.71
Permanent Ineff=
       F       F
Bank Sta=286.7,301.7
XS Rating Curve= 0 ,0
Exp/Cntr=0.3,0.1

Type RM Length L Ch R = 1 ,11443   ,275.9,280.8,285.7
XS GIS Cut Line= 3
     2028118.427      287292.035     2027846.292      287702.192
     2027815.042        287832.4
#Sta/Elev= 30
       0  1669.8     6.5  1665.7    19.6 1652.83    22.8 1650.89    26.1 1650.03
    61.9 1649.66    81.5 1651.12     101  1651.3  157.521649.866  180.561650.028
     238 1649.35   296.6 1647.05  342.341647.807   348.8 1646.81   358.6 1643.99
   361.8 1643.85   379.5 1644.11   394.4  1644.9   397.7 1646.52   404.2 1653.39
   407.5 1655.82     427 1658.41   453.1 1664.19   472.7 1671.73  479.62 1673.61
   485.7 1675.42  508.941686.918     538 1701.84   590.2 1730.52   626.1 1751.54
#Mann= 8 ,-1 , 0
       0     .12       0  157.52     .08       0  180.56     .06       0
  342.34     .12       0   358.6    .045       0   379.5     .12       0
  479.62     .08       0  508.94     .12       0
#XS Ineff= 2 , 0
          264.49 1655.29
Permanent Ineff=
       F       F
Bank Sta=358.6,379.5
XS Rating Curve= 0 ,0
Exp/Cntr=0.3,0.1

Type RM Length L Ch R = 1 ,11162.2 ,187.8,185.9,184.1
XS GIS Cut Line= 3
      2028045.51      287087.608     2027600.198      287517.296
     2027617.125      287703.494
#Sta/Elev= 30
       0 1701.81    29.5 1689.02   39.021682.406    42.6  1680.7    65.5 1679.35
   80.82 1670.43      95 1662.59   101.5 1657.71   111.3 1648.16   117.9 1645.36
   140.8 1645.41   157.2 1648.62  242.621648.206  270.741647.019   314.3 1645.09
   386.4 1645.59  414.881640.782   419.1 1639.43   428.9 1638.44   438.7 1639.31
   468.2 1641.69   481.3 1647.65     5711647.524   638.5 1652.45   687.7 1660.03
   707.4 1664.32   756.6 1681.54   792.7 1700.37   802.5 1703.16   805.8 1705.37
#Mann= 9 ,-1 , 0
       0     .12       0   39.02    .016       0   80.82     .12       0
  242.62     .08       0  270.74     .06       0  414.88     .12       0
   419.1    .045       0   438.7     .12       0     571     .06       0
Bank Sta=419.1,438.7
XS Rating Curve= 0 ,0
Exp/Cntr=0.3,0.1

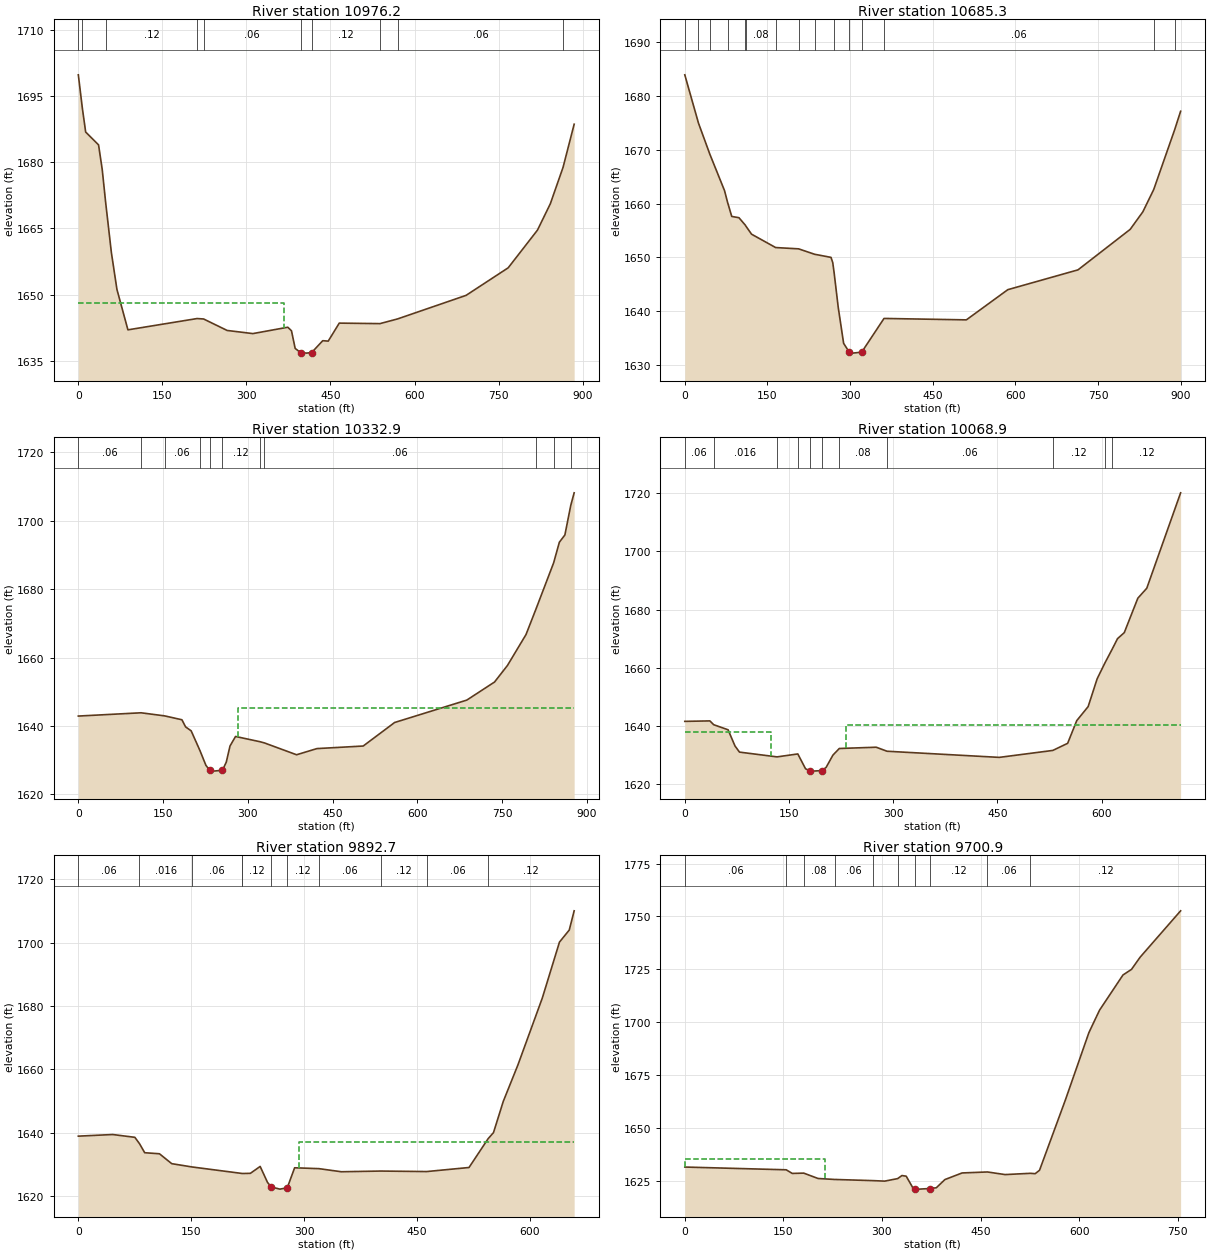
Type RM Length L Ch R = 1 ,10976.2 ,297.9,290.9,283.8
XS GIS Cut Line= 3
     2027863.219      286960.004     2027406.187      287479.535
     2027416.604      287672.244
#Sta/Elev= 30
       0 1699.75     7.11692.283    13.1  1686.8    36.1  1683.9    42.6 1678.38
   48.881670.736      59 1659.51    68.9 1651.19    88.5 1642.04  211.951644.595
  223.631644.494   265.6  1641.9   311.5 1641.19   373.8 1642.63   380.4 1641.83
     387 1637.83   396.7 1636.89   406.6 1636.77   416.5 1636.91   436.2 1639.58
     446 1639.49   465.7 1643.56  538.341643.447  569.721644.508     692 1649.84
   767.2 1656.08   819.5 1664.62   842.4 1670.58  865.121678.825   884.9 1688.57
#Mann= 10 ,-1 , 0
       0     .12       0     7.1    .016       0   48.88     .12       0
  211.95     .08       0  223.63     .06       0   396.7    .045       0
   416.5     .12       0  538.34     .08       0  569.72     .06       0
  865.12     .12       0
#XS Ineff= 2 , 0
           367.9 1648.01
Permanent Ineff=
       F       F
Bank Sta=396.7,416.5
XS Rating Curve= 0 ,0
Exp/Cntr=0.3,0.1

Type RM Length L Ch R = 1 ,10685.3 ,365.8,352.5,339.1
XS GIS Cut Line= 3
     2027502.252       286790.82     2027293.919      287268.251
     2027363.219      287640.994
#Sta/Elev= 30
       0 1683.93   24.831674.958    45.51669.173    72.1 1662.42   77.731660.214
    85.2 1657.62    98.3 1657.38  110.021655.979  110.841655.825   121.2 1654.32
   164.91651.837  206.641651.595  235.471650.593   265.4 1650.01   268.6 1649.02
  271.091647.126   278.5 1640.73   288.3 1634.04   298.3 1632.43   304.7 1632.22
   321.1  1632.4  361.621638.665   511.1  1638.4   586.3 1644.01   713.7 1647.69
   808.5 1655.22   831.4 1658.47  851.171662.617   888.91673.649     900 1677.16
#Mann= 15 ,-1 , 0
       0     .12       0   24.83     .08       0    45.5     .06       0
   77.73    .016       0  110.02     .12       0  110.84     .08       0
   164.9     .06       0  206.64    .016       0  235.47     .08       0
  271.09     .12       0   298.3    .045       0   321.1     .08       0
  361.62     .06       0  851.17     .08       0   888.9     .12       0
Bank Sta=298.3,321.1
XS Rating Curve= 0 ,0
Exp/Cntr=0.3,0.1

Type RM Length L Ch R = 1 ,10332.9 ,263.2,264,264.8
XS GIS Cut Line= 3
     2026990.099      286803.841     2027118.138      287509.136
     2027081.245      287665.386
#Sta/Elev= 30
       0  1642.9  110.991643.855  152.621642.957   183.3 1641.82   189.8 1639.74
   199.7 1638.58  215.36 1632.77   225.8  1628.5   232.4  1627.1   238.9 1626.82
     255 1627.07   261.8 1629.44   268.4 1634.15   278.2 1636.94  321.761635.397
  329.351635.053   386.2  1631.6   422.2  1633.4   504.1 1634.15   559.7 1641.02
   687.4 1647.56   736.5 1652.84   759.4 1657.68   792.2  1666.7  809.98 1674.21
  841.051687.624   851.2 1693.66     861 1695.78   871.41704.427   877.4 1708.09
#Mann= 11 ,-1 , 0
       0     .06       0  110.99    .016       0  152.62     .06       0
  215.36     .12       0   232.4    .045       0     255     .12       0
  321.76     .08       0  329.35     .06       0  809.98     .12       0
  841.05     .06       0   871.4     .12       0
#XS Ineff= 2 , 0
                          282.67         1645.22
Permanent Ineff=
       F       F
Bank Sta=232.4,255
XS Rating Curve= 0 ,0
Exp/Cntr=0.3,0.1

Type RM Length L Ch R = 1 ,10068.9 ,175.4,176.2,176.9
XS GIS Cut Line= 3
     2026747.333      286907.921     2026833.271       287488.65
     2026825.458      287614.952
#Sta/Elev= 30
       0  1641.6    36.1 1641.76   41.621640.451    62.3 1638.71    72.2 1633.17
    78.7 1631.04  132.791629.402  162.651630.413   173.8 1625.31   179.7 1624.67
   183.7 1624.51   196.8 1624.69   203.3 1625.76   213.2 1630.01  222.361632.283
   275.5 1632.72  291.091631.339   452.6 1629.23  529.69 1631.62     551 1634.06
   564.1 1641.85   580.5 1646.67   593.5 1656.24  604.551661.609  615.321666.501
   622.8 1670.01   632.5 1672.07     652 1683.89   664.9 1687.33   713.6 1720.09
#Mann= 11 ,-1 , 0
       0     .06       0   41.62    .016       0  132.79     .06       0
  162.65     .08       0   179.7    .045       0   196.8     .06       0
  222.36     .08       0  291.09     .06       0  529.69     .12       0
  604.55     .06       0  615.32     .12       0
#XS Ineff= 2 , 0
          123.86 1637.89  231.82         1640.33
Permanent Ineff=
       F       F
Bank Sta=179.7,196.8
XS Rating Curve= 0 ,0
Exp/Cntr=0.3,0.1

Type RM Length L Ch R = 1 ,9892.7  ,191.7,191.8,191.9
XS GIS Cut Line= 3
     2026576.167      286881.799     2026633.184      287381.445
     2026616.257      287536.393
#Sta/Elev= 30
       0 1638.96    45.7 1639.47    75.1 1638.59   81.241636.597    88.2 1633.73
   107.8  1633.4   124.1 1630.28  150.971629.244  217.821627.182  217.95 1627.18
   228.6 1627.23   241.6 1629.41   251.4 1624.35   256.4 1622.92   267.8 1622.25
   277.6 1622.67   287.4 1628.98  319.731628.706   349.4 1627.73  401.741627.949
   462.81627.789   519.1 1629.07  544.531638.171   551.6 1640.06   564.6 1649.91
   584.1 1661.43   616.5 1682.53   639.3 1700.16   652.3 1703.96   658.8 1710.02
#Mann= 11 ,-1 , 0
       0     .06       0   81.24    .016       0  150.97     .06       0
  217.82     .08       0  217.95     .12       0   256.4    .045       0
   277.6     .12       0  319.73     .06       0  401.74     .12       0
   462.8     .06       0  544.53     .12       0
#XS Ineff= 2 , 0
                          293.32         1637.07
Permanent Ineff=
       F       F
Bank Sta=256.4,277.6
XS Rating Curve= 0 ,0
Exp/Cntr=0.3,0.1

Type RM Length L Ch R = 1 ,9700.9  ,201.5,201.5,201.3
XS GIS Cut Line= 3
      2026380.29      286829.882     2026446.552      287424.848
     2026429.625      287579.796
#Sta/Elev= 30
       0 1631.68   154.31630.378   163.6 1628.66  180.961628.809   202.8 1626.27
  228.091625.814  286.511625.261   304.2 1625.03  323.961626.223   330.4 1627.66
   336.9 1627.37   346.8    1622     350 1621.48   356.6 1621.25     373 1621.54
   382.7 1621.89   395.8 1625.76     422 1628.89  460.511629.353   487.4 1628.12
  525.891628.713   533.2 1628.54   539.8 1630.16     579 1663.23   614.9 1695.14
   631.1 1705.75   666.8 1722.38   679.8 1725.03   692.8 1730.75   754.5 1752.67
#Mann= 10 ,-1 , 0
       0     .06       0   154.3    .016       0  180.96     .08       0
  228.09     .06       0  286.51     .08       0  323.96     .12       0
     350    .045       0     373     .12       0  460.51     .06       0
  525.89     .12       0
#XS Ineff= 2 , 0
          213.64 1635.34
Permanent Ineff=
       F       F
Bank Sta=350,373
XS Rating Curve= 0 ,0
Exp/Cntr=0.3,0.1

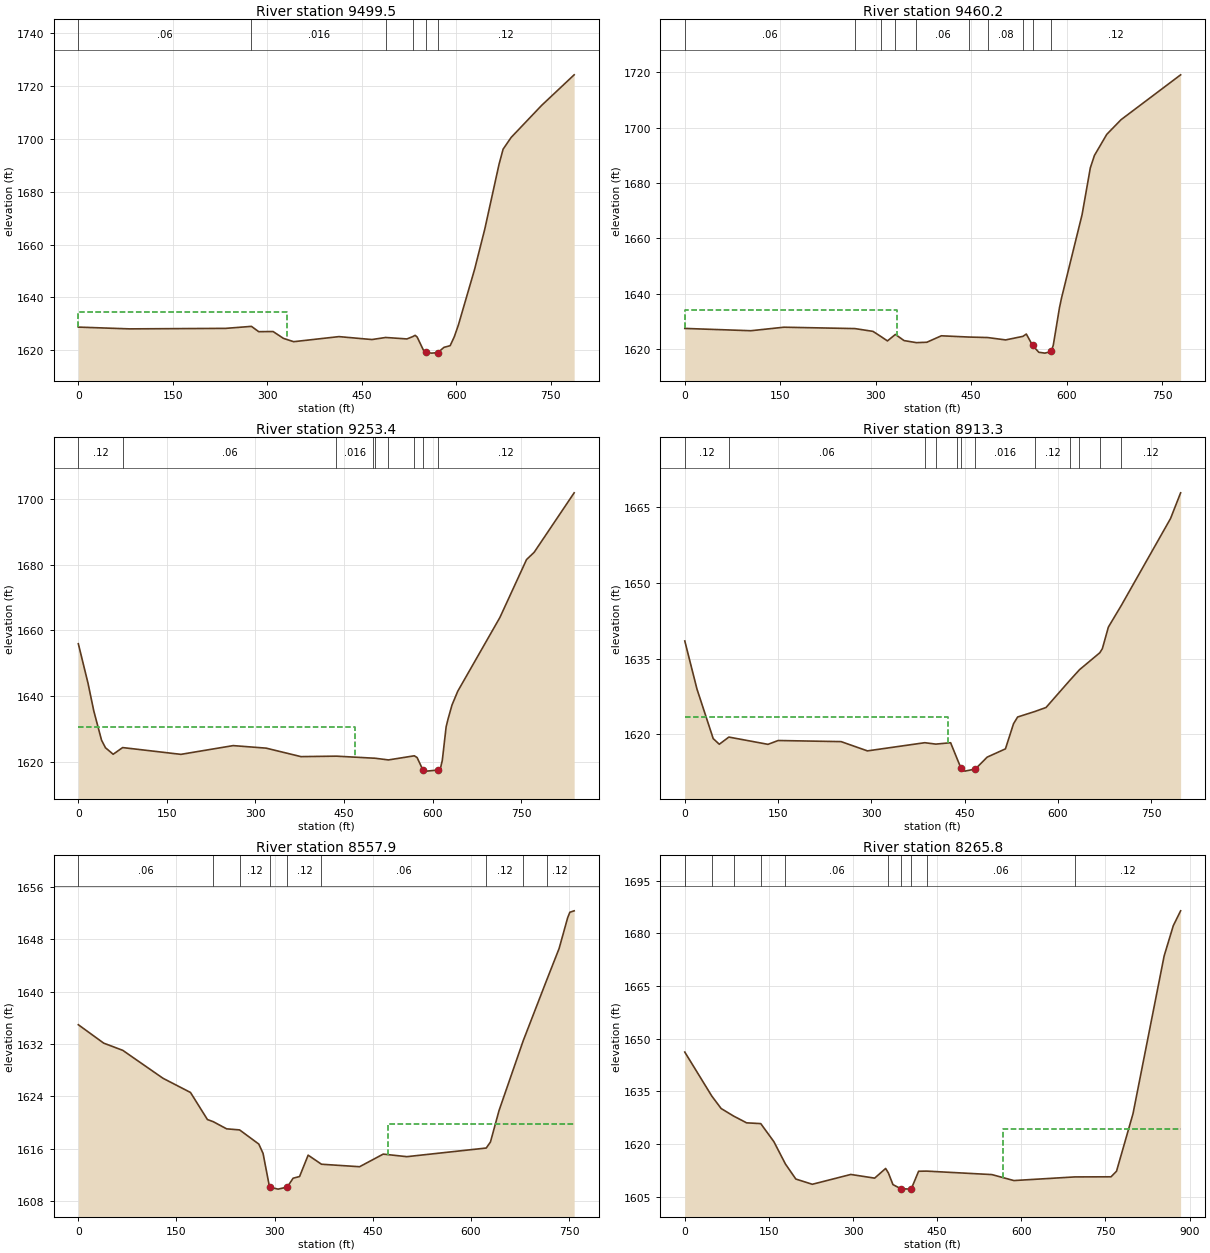
Type RM Length L Ch R = 1 ,9499.5  ,39.3,39.3,39.3
XS GIS Cut Line= 4
     2026163.277      286734.396     2026203.105      286931.789
     2026249.937      287331.098       2026226.5      287513.389
#Sta/Elev= 30
       0 1628.79    81.2 1628.12   234.1 1628.31  274.821629.071   286.4 1627.06
   309.2 1627.12   325.6 1624.53   341.9 1623.27   413.8 1625.19   466.1 1624.08
  488.031624.864   521.7 1624.31  530.581625.159   534.8 1625.68     538 1625.01
   547.8 1620.11   551.8 1619.28   560.9 1618.94   570.7 1619.13   580.5 1621.12
   590.3 1621.76   596.9 1625.13   603.4 1629.59   629.2 1650.71   645.3 1665.88
   667.9 1690.38   674.4 1696.14   687.2 1700.59   735.6 1712.72   787.2 1724.28
#Mann= 6 ,-1 , 0
       0     .06       0  274.82    .016       0  488.03     .08       0
  530.58     .12       0   551.8    .045       0   570.7     .12       0
#XS Ineff= 2 , 0
          330.68  1634.6
Permanent Ineff=
       F       F
Bank Sta=551.8,570.7
XS Rating Curve= 0 ,0
Exp/Cntr=0.3,0.1

Type RM Length L Ch R = 1 ,9460.2  ,208.1,206.7,205.4
XS GIS Cut Line= 4
     2026119.874      286747.417     2026165.348      286946.827
     2026210.875      287335.004     2026187.437      287517.296
#Sta/Elev= 30
       0 1627.45   103.9 1626.62   155.8 1627.89  267.391627.392   295.7 1626.39
  307.61 1624.62   318.5 1622.94  330.941625.282   344.6 1623.06  363.881622.316
   380.4 1622.46   403.2 1624.79   446.31624.338  476.041624.157   504.2  1623.3
  531.351624.587   536.7 1625.42   546.5 1621.34   556.3 1618.84     566 1618.53
   575.8 1619.12   579.1  1621.4   588.8 1634.91   592.1 1638.49   624.4 1668.62
   637.3 1685.43   643.7  1689.9   663.1 1697.53   685.6 1702.84   779.2 1719.04
#Mann= 10 ,-1 , 0
       0     .06       0  267.39    .016       0  307.61     .12       0
  330.94     .08       0  363.88     .06       0   446.3    .016       0
  476.04     .08       0  531.35     .12       0   546.5    .045       0
   575.8     .12       0
#XS Ineff= 2 , 0
          334.09 1633.94
Permanent Ineff=
       F       F
Bank Sta=546.5,575.8
XS Rating Curve= 0 ,0
Exp/Cntr=0.3,0.1

Type RM Length L Ch R = 1 ,9253.4  ,342.1,340.1,338.1
XS GIS Cut Line= 3
     2025894.179      286693.164     2026011.656      287351.497
     2026084.573      287506.011
#Sta/Elev= 30
       0 1655.95    16.4 1643.95    26.2  1635.5    39.3 1626.64    45.9 1624.34
      59 1622.35   75.051624.383   173.7 1622.32   262.2 1624.98     318 1624.21
     377 1621.63  437.091621.773  498.931621.168  501.59 1621.16   525.21620.625
  568.981621.884   573.7 1621.34   583.5 1617.56   590.1 1617.22     609 1617.56
     613 1617.94   616.3 1620.45   622.8 1630.68   626.1 1633.09   632.7  1637.3
   642.5 1641.52   713.9 1663.96     759 1681.56   771.9 1683.77   839.6 1701.85
#Mann= 9 ,-1 , 0
       0     .12       0   75.05     .06       0  437.09    .016       0
  498.93     .08       0  501.59     .12       0   525.2    .016       0
  568.98     .12       0   583.5    .045       0     609     .12       0
#XS Ineff= 2 , 0
          468.75 1630.73
Permanent Ineff=
       F       F
Bank Sta=583.5,609
XS Rating Curve= 0 ,0
Exp/Cntr=0.3,0.1

Type RM Length L Ch R = 1 ,8913.3  ,371.5,355.4,339.6
XS GIS Cut Line= 3
     2025551.297      286853.754     2025695.684      287443.511
     2025825.892        287582.4
#Sta/Elev= 30
       0 1638.49    19.6 1628.93    45.7  1619.1    55.5 1617.98   70.891619.403
   133.8 1617.96   150.2 1618.72   251.4  1618.5   293.8 1616.66  386.051618.284
  403.851618.004   427.6 1618.28  438.551614.953     444 1613.32   450.5 1612.64
   467.3 1613.05   486.4 1615.42   515.8 1617.06   528.8 1622.05   535.4 1623.39
  562.751624.466   581.1 1625.28  619.891630.737  634.92 1632.78  667.591636.145
   671.7 1636.96   681.4 1641.25  702.381645.586   781.4 1662.81   797.6 1667.91
#Mann= 12 ,-1 , 0
       0     .12       0   70.89     .06       0  386.05    .016       0
  403.85     .08       0  438.55    .016       0     444    .045       0
   467.3    .016       0  562.75     .12       0  619.89     .06       0
  634.92     .12       0  667.59     .08       0  702.38     .12       0
#XS Ineff= 2 , 0
          423.86  1623.3
Permanent Ineff=
       F       F
Bank Sta=444,467.3
XS Rating Curve= 0 ,0
Exp/Cntr=0.3,0.1

Type RM Length L Ch R = 1 ,8557.9  ,291.7,292.1,292.2
XS GIS Cut Line= 3
     2025070.091      287252.893     2025274.084      287315.827
     2025721.132      287626.157
#Sta/Elev= 30
       0 1634.95    38.8 1632.13    67.9 1631.03   129.4 1626.75   171.4 1624.58
   197.3 1620.43  206.091620.111   226.6 1619.01  246.441618.846   275.8 1616.68
   282.3 1615.25   292.2 1610.08   305.3 1609.78   319.3  1610.1   328.2 1611.45
   338.1 1611.71   351.2 1614.98  371.571613.591   429.8 1613.21   465.9 1615.14
     502 1614.75  623.371616.073   629.8    1617   642.9 1621.81   679.71632.458
  715.511641.726   734.7 1646.62   747.8 1651.34   751.1 1652.17   757.7 1652.39
#Mann= 9 ,-1 , 0
       0     .06       0  206.09    .016       0  246.44     .12       0
   292.2    .045       0   319.3     .12       0  371.57     .06       0
  623.37     .12       0   679.7    .016       0  715.51     .12       0
#XS Ineff= 2 , 0
                          473.86          1619.8
Permanent Ineff=
       F       F
Bank Sta=292.2,319.3
XS Rating Curve= 0 ,0
Exp/Cntr=0.3,0.1

Type RM Length L Ch R = 1 ,8265.8  ,321.9,321.9,320.5
XS GIS Cut Line= 3
     2024850.343       287411.48     2024997.912      287470.073
     2025583.849      287897.591
#Sta/Elev= 30
       0 1646.22     .391646.105   48.251633.662    64.8 1630.14   87.031627.987
   110.2 1626.06  135.43 1625.84   158.8 1620.71  179.53 1614.31     198 1610.05
   227.4 1608.56     296 1611.36   338.5 1610.31   358.1 1613.06  363.011611.789
   371.2 1608.46   384.8 1607.34   400.6 1607.18   403.8 1607.23   416.9 1612.27
  431.131612.312   547.6 1611.32   586.8 1609.62  695.591610.657     760 1610.69
   769.8 1612.28   799.2 1628.66   854.7 1673.58     871  1682.2   884.1 1686.44
#Mann= 11 ,-1 , 0
       0     .12       0     .39    .016       0   48.25     .06       0
   87.03    .016       0  135.43     .08       0  179.53     .06       0
  363.01     .12       0   384.8    .045       0   403.8     .12       0
  431.13     .06       0  695.59     .12       0
#XS Ineff= 2 , 0
                          568.18         1624.33
Permanent Ineff=
       F       F
Bank Sta=384.8,403.8
XS Rating Curve= 0 ,0
Exp/Cntr=0.3,0.1