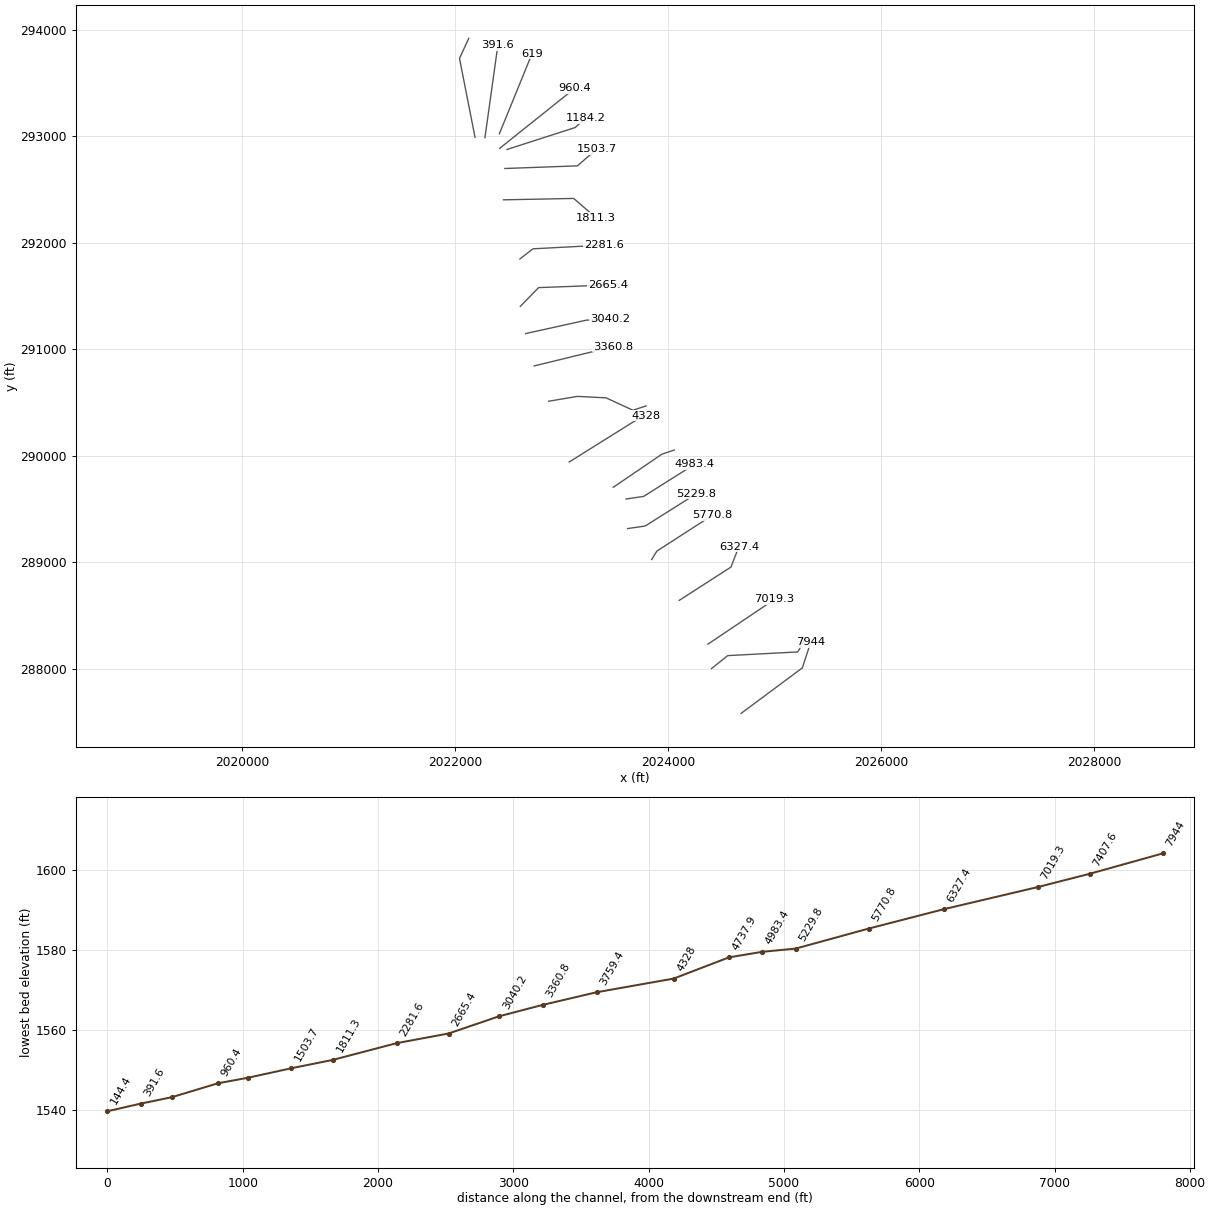
HEC-RAS study LICKCK1.prj: LICKCK1

--- LICKCK1.g01 (geometry) --- (continued)

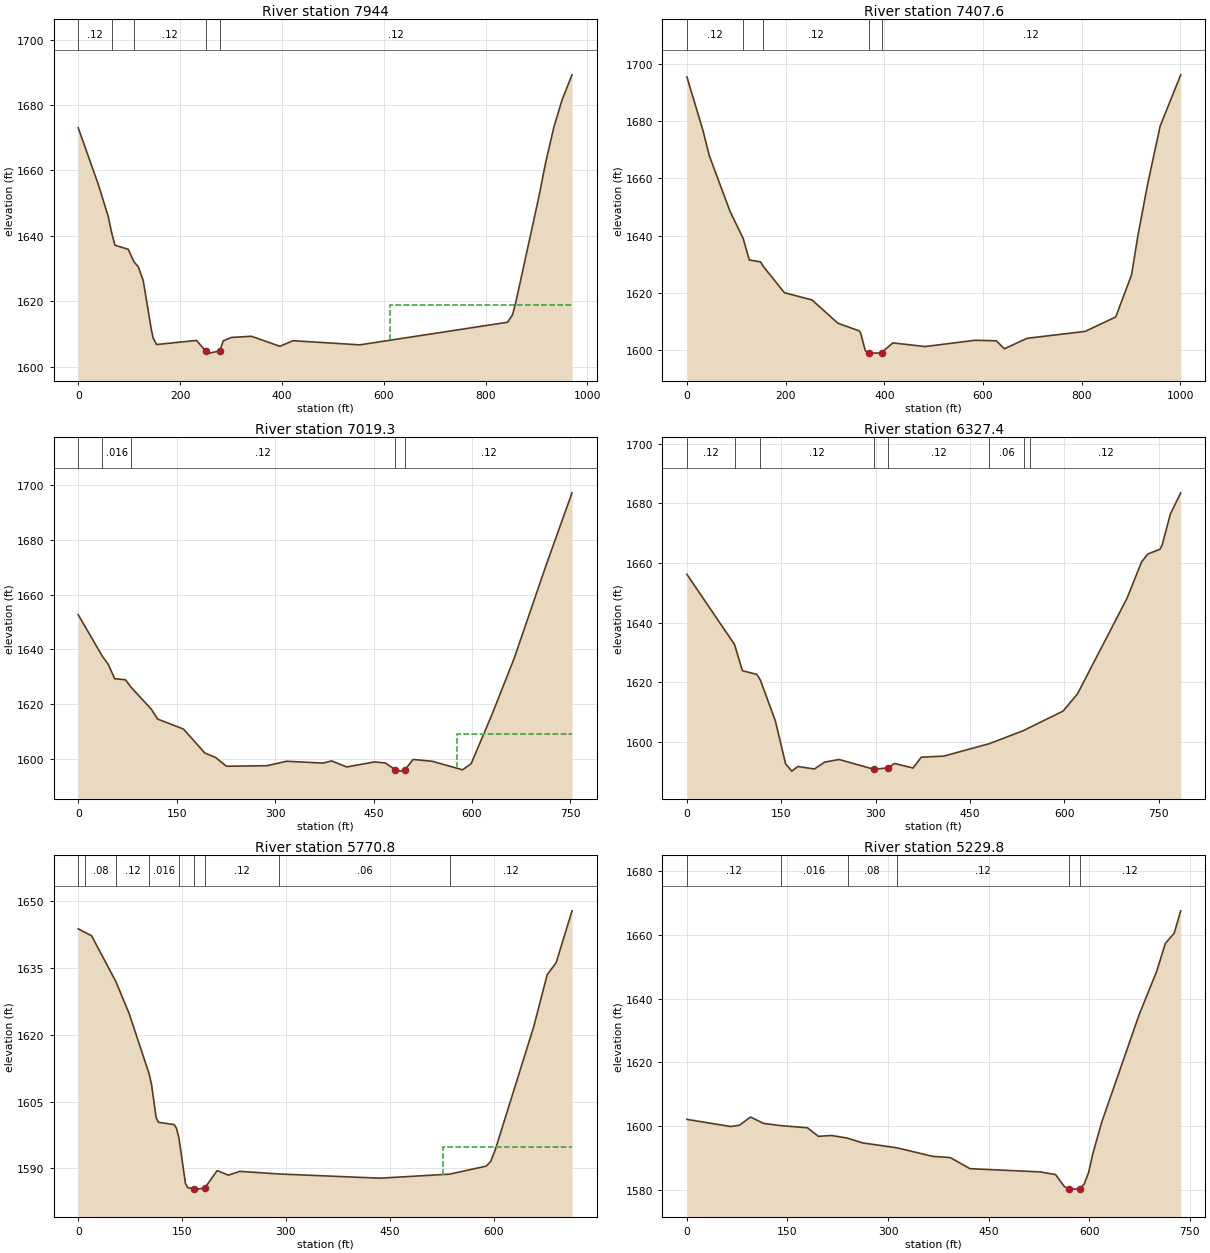
Type RM Length L Ch R = 1 ,7944    ,549.1,536.4,525
XS GIS Cut Line= 3
     2024685.412       287578.58     2025260.499      288006.098
     2025338.624      288246.983
#Sta/Elev= 30
       0 1673.03    39.3 1655.78    58.9 1645.93   65.381641.137      72 1637.12
    98.2 1635.88  109.53 1632.02   117.8 1630.55   127.6 1626.33     144 1610.95
   147.2 1608.72   153.8 1606.74   232.3    1608     250 1604.81   258.5 1604.11
   278.1 1604.83   284.7 1607.85     301 1608.91   340.3 1609.26   395.9 1606.21
   422.1 1607.91     553 1606.64   843.2 1613.56     853 1615.85   859.4 1619.69
   904.9 1652.09   917.9 1662.35   934.1 1673.21   950.3 1681.61   969.8 1689.25
#Mann= 5 ,-1 , 0
       0     .12       0   65.38    .016       0  109.53     .12       0
     250    .045       0   278.1     .12       0
#XS Ineff= 2 , 0
                          612.22         1618.85
Permanent Ineff=
       F       F
Bank Sta=250,278.1
XS Rating Curve= 0 ,0
Exp/Cntr=0.3,0.1

Type RM Length L Ch R = 1 ,7407.6  ,376.2,388.3,400
XS GIS Cut Line= 4
     2024407.634      287999.587     2024559.544      288121.115
     2025217.096      288155.837     2025290.881      288283.876
#Sta/Elev= 30
       0 1695.36    32.4 1676.78    45.4 1667.88    87.5 1648.43  113.971639.051
   126.4 1631.54   149.2 1630.86  154.711629.289   197.8 1620.09   253.5  1617.6
   305.9 1609.47   348.5 1606.85   351.8 1606.17   361.6 1599.87   368.2 1599.16
   387.8 1599.04   394.4 1599.22   417.3  1602.6   482.8 1601.34   584.4 1603.53
     627 1603.34   643.4 1600.55   689.2  1604.2   807.1 1606.62   869.1 1611.66
   901.2 1626.37     914 1639.98   933.3 1657.62     959 1678.16  1000.8  1696.1
#Mann= 5 ,-1 , 0
       0     .12       0  113.97    .016       0  154.71     .12       0
   368.2    .045       0   394.4     .12       0
Bank Sta=368.2,394.4
XS Rating Curve= 0 ,0
Exp/Cntr=0.3,0.1

Type RM Length L Ch R = 1 ,7019.3  ,687.9,691.9,686.9
XS GIS Cut Line= 2
     2024374.211      288229.143     2024998.783      288648.938
#Sta/Elev= 30
       0 1652.67   36.861637.493    45.8  1634.6    55.6 1629.34      72 1628.99
   80.02 1626.36   111.2  1618.3   121.1 1614.64   160.3 1611.02     193 1602.27
   209.4 1600.65   225.8 1597.46   287.9 1597.66   317.4 1599.28     373 1598.61
   386.1 1599.41     409  1597.2   451.5 1599.04   467.9 1598.65   482.9 1596.21
   490.8 1595.68   497.9 1596.19   510.4 1599.94   539.9 1599.25   585.7 1596.16
   598.8 1598.39   631.5  1616.9   664.2 1636.68   713.3 1670.91   752.5 1697.08
#Mann= 5 ,-1 , 0
       0     .12       0   36.86    .016       0   80.02     .12       0
   482.9    .045       0   497.9     .12       0
#XS Ineff= 2 , 0
                          577.27         1609.04
Permanent Ineff=
       F       F
Bank Sta=482.9,497.9
XS Rating Curve= 0 ,0
Exp/Cntr=0.3,0.1

Type RM Length L Ch R = 1 ,6327.4  ,554.7,556.6,555.2
XS GIS Cut Line= 3
     2024103.815      288639.778     2024590.215       288953.06
     2024664.868      289145.768
#Sta/Elev= 30
       0 1656.16    75.7 1632.66    88.2 1623.84   111.1 1622.63  116.941620.623
   140.6 1607.03   156.9  1592.6   166.7 1590.16   176.5 1591.72   202.7 1590.87
     219 1593.18   241.9 1594.07   297.4 1590.78   319.9 1591.25   330.1 1592.73
   359.6  1591.2   372.6 1594.83   408.6 1595.21  480.771599.361  535.321603.772
  545.781604.887   598.2 1610.31   621.2 1616.13   699.9  1648.2   722.9 1660.31
   732.7 1662.97   752.4 1664.62   755.7 1666.06   768.8 1676.45   785.2 1683.52
#Mann= 8 ,-1 , 0
       0     .12       0    75.7    .016       0  116.94     .12       0
   297.4    .045       0   319.9     .12       0  480.77     .06       0
  535.32     .08       0  545.78     .12       0
Bank Sta=297.4,319.9
XS Rating Curve= 0 ,0
Exp/Cntr=0.3,0.1

Type RM Length L Ch R = 1 ,5770.8  ,539.6,541,539.3
XS GIS Cut Line= 3
     2023845.568      289023.893     2023894.469      289102.799
     2024415.302      289439.605
#Sta/Elev= 30
       0 1643.83    9.761643.045    19.2  1642.3   54.281632.009    73.6 1624.76
  102.481611.199   105.9 1608.79   112.4  1601.5   115.7 1600.34   138.5 1599.81
   141.8 1599.02  145.291596.952   154.8 1586.63   158.1 1585.63   167.5 1585.39
   171.2  1585.3   182.5 1585.51   200.6 1589.47   216.9 1588.44   233.2  1589.3
  290.151588.707   435.6 1587.76  536.161588.668     589 1590.46   595.6 1591.51
   602.1 1594.08   657.6 1621.74   677.2  1633.5   690.2 1636.24   713.1 1647.89
#Mann= 9 ,-1 , 0
       0     .12       0    9.76     .08       0   54.28     .12       0
  102.48    .016       0  145.29     .12       0   167.5    .045       0
   182.5     .12       0  290.15     .06       0  536.16     .12       0
#XS Ineff= 2 , 0
                          526.14          1594.8
Permanent Ineff=
       F       F
Bank Sta=167.5,182.5
XS Rating Curve= 0 ,0
Exp/Cntr=0.3,0.1

Type RM Length L Ch R = 1 ,5229.8  ,246.3,246.5,246.4
XS GIS Cut Line= 3
     2023619.874      289314.692     2023784.804      289338.563
     2024266.864       289642.73
#Sta/Elev= 30
       0 1602.15    65.4 1599.91    78.4 1600.31    94.8 1602.88   114.4 1600.89
  140.241600.186   179.8 1599.52   196.1 1596.83   215.8  1597.1  239.791596.254
   261.6 1594.79  313.191593.238   366.5 1590.56   392.7 1590.18   422.2  1586.7
     527 1585.68   549.9 1584.84     563 1581.08   569.3 1580.43   579.4 1580.28
     586 1580.47   592.5 1581.83   599.1 1585.42   605.6 1591.47   618.7 1601.24
   674.4 1634.88   700.6 1648.49   713.7 1657.35   726.8 1660.51   736.6 1667.54
#Mann= 6 ,-1 , 0
       0     .12       0  140.24    .016       0  239.79     .08       0
  313.19     .12       0   569.3    .045       0     586     .12       0
Bank Sta=569.3,586
XS Rating Curve= 0 ,0
Exp/Cntr=0.3,0.1

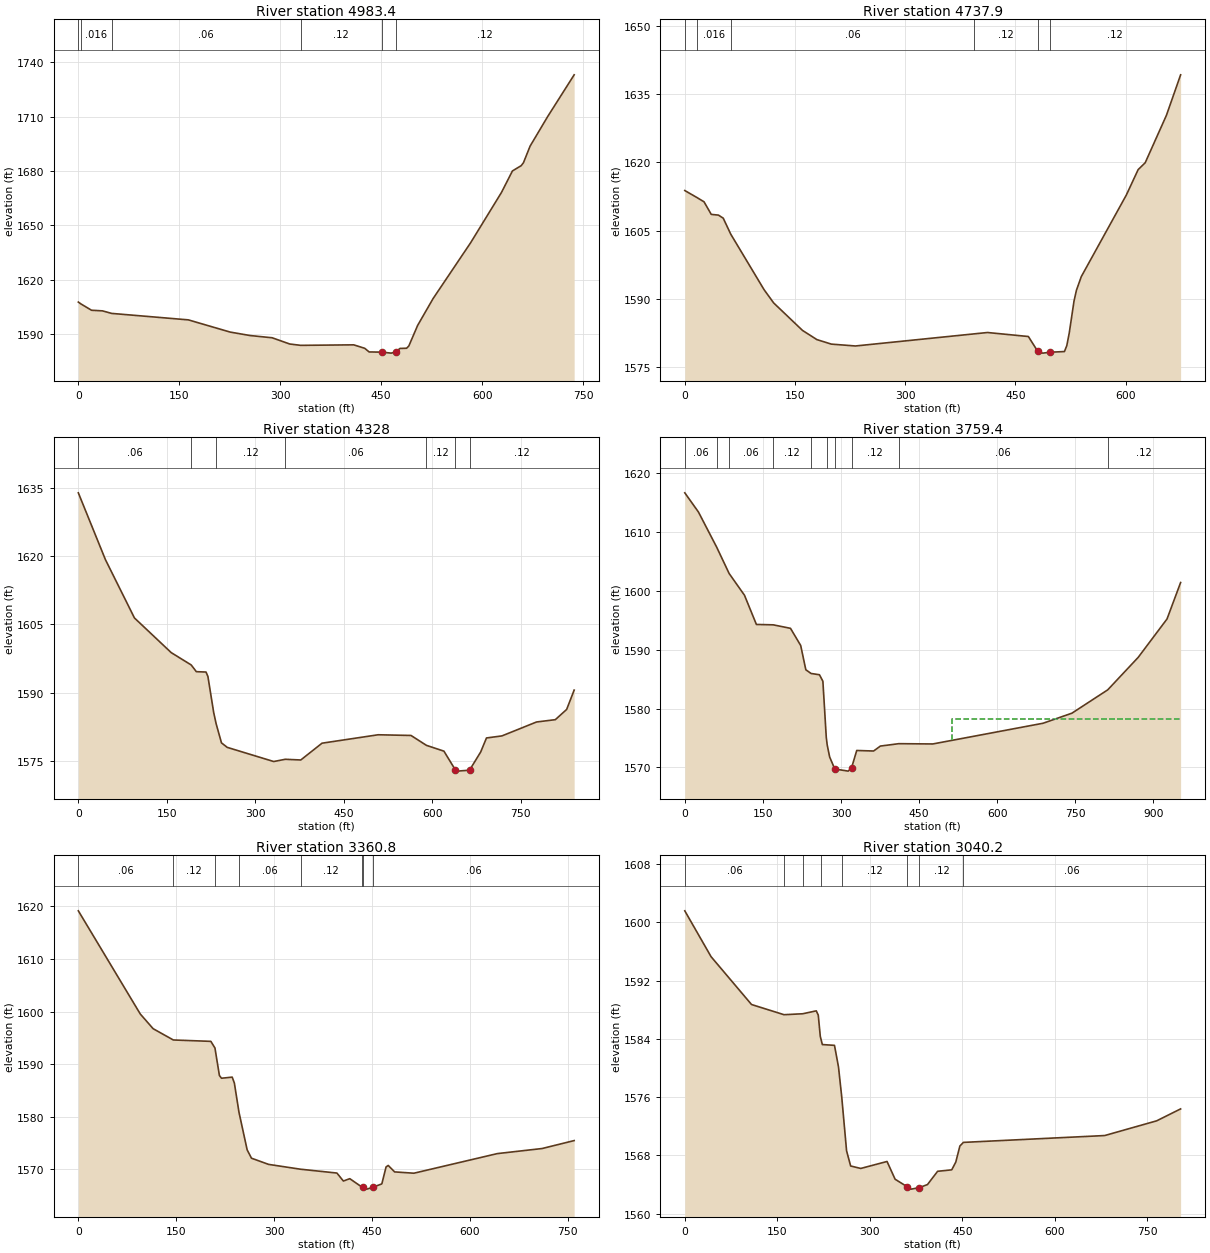
Type RM Length L Ch R = 1 ,4983.4  ,244.6,245.5,246.1
XS GIS Cut Line= 3
     2023604.683      289592.469     2023769.613      289616.341
     2024251.674      289920.507
#Sta/Elev= 30
       0 1607.65    4.091606.574    19.6 1603.14    35.9  1602.8   49.481601.398
   163.4 1597.83   225.6 1591.09   255.1 1589.19   287.9 1587.96   314.1 1584.51
  330.34 1583.77   409.1 1584.05   425.4 1582.15     432 1580.14   450.9 1580.02
   464.8 1579.48   471.3  1580.1   477.9 1582.07   487.7 1582.18     491 1583.44
   504.1 1594.79     527 1609.56   582.7 1640.33   628.6 1668.12   644.9    1680
     658 1682.94   661.3 1684.57   671.1 1693.67   697.3 1710.03   736.6 1733.04
#Mann= 6 ,-1 , 0
       0     .12       0    4.09    .016       0   49.48     .06       0
  330.34     .12       0   450.9    .045       0   471.3     .12       0
Bank Sta=450.9,471.3
XS Rating Curve= 0 ,0
Exp/Cntr=0.3,0.1

Type RM Length L Ch R = 1 ,4737.9  ,410.2,409.9,408.8
XS GIS Cut Line= 3
     2023485.614      289702.626     2023942.381      290013.699
     2024058.242      290052.539
#Sta/Elev= 30
       0 1613.82   16.821612.256    26.2 1611.34      36 1608.58    45.8 1608.42
    52.3 1607.75   62.511604.243   107.9 1592.03     121 1589.11   160.2 1583.08
   179.8 1581.06   199.5 1580.07   232.2 1579.66  394.27 1582.33     412 1582.62
   467.6 1581.74   480.4 1578.47   487.2 1578.09     497 1578.28   516.7 1578.44
   519.9 1579.75   523.2 1582.49   529.7 1589.52     533  1591.9   539.6  1594.9
   600.9 1612.83     617 1618.42   626.6 1619.93   655.5 1630.36   674.8 1639.25
#Mann= 6 ,-1 , 0
       0     .06       0   16.82    .016       0   62.51     .06       0
  394.27     .12       0   480.4    .045       0     497     .12       0
Bank Sta=480.4,497
XS Rating Curve= 0 ,0
Exp/Cntr=0.3,0.1

Type RM Length L Ch R = 1 ,4328    ,582.5,568.7,552.9
XS GIS Cut Line= 3
     2023071.312      289939.941     2023715.944      290343.511
     2023789.385      290374.685
#Sta/Elev= 30
       0 1633.94    45.9 1619.26    95.1 1606.44   157.4 1598.82  191.281596.107
     200 1594.63   216.4 1594.55   219.6 1593.59   229.5 1585.58  233.641583.136
   242.6 1578.98   252.4 1577.99   331.1 1574.88   350.71575.373     377 1575.22
     413 1578.91   508.1 1580.76   563.8 1580.61  589.981578.433   619.6 1577.16
   639.2 1572.99   642.5 1572.77     663 1572.98   681.9 1576.98   691.7 1580.06
   717.9 1580.51   776.5 1583.57   808.4 1584.08   827.6 1586.33   840.3 1590.58
#Mann= 7 ,-1 , 0
       0     .06       0  191.28    .016       0  233.64     .12       0
   350.7     .06       0  589.98     .12       0   639.2    .045       0
     663     .12       0
Bank Sta=639.2,663
XS Rating Curve= 0 ,0
Exp/Cntr=0.3,0.1

Type RM Length L Ch R = 1 ,3759.4  ,391.9,398.6,404.4
XS GIS Cut Line= 5
     2022877.686      290510.438     2023148.809      290556.358
     2023417.906      290542.469     2023669.642       290426.15
     2023793.485      290467.035
#Sta/Elev= 30
       0 1616.68    26.2 1613.42   61.231607.439   85.131602.967   114.6 1599.27
   137.5  1594.3  169.981594.232     203 1593.64   222.6 1590.72   232.4  1586.6
   242.51585.963   258.6 1585.75   265.2 1584.64   271.7  1575.1  273.481573.816
   278.2 1571.76     288 1569.72   313.9 1569.36   320.4 1569.96   330.2 1572.87
   362.6 1572.78   375.6 1573.62  410.981574.027   476.3 1573.98     688  1577.5
   743.4 1579.21  812.23 1583.18   870.7  1588.7   926.1 1595.23   952.2 1601.43
#Mann= 10 ,-1 , 0
       0     .06       0   61.23     .08       0   85.13     .06       0
  169.98     .12       0   242.5    .016       0  273.48     .12       0
     288    .045       0   320.4     .12       0  410.98     .06       0
  812.23     .12       0
#XS Ineff= 2 , 0
                          512.78         1578.19
Permanent Ineff=
       F       F
Bank Sta=288,320.4
XS Rating Curve= 0 ,0
Exp/Cntr=0.3,0.1

Type RM Length L Ch R = 1 ,3360.8  ,321.1,320.5,319.8
XS GIS Cut Line= 2
     2022743.138      290842.469     2023480.985      291022.591
#Sta/Elev= 30
       0 1619.17    94.9 1599.53   114.6 1596.73  145.521594.583     203 1594.32
  209.271593.059   216.1 1587.82   219.3  1587.3   235.7 1587.51     239 1586.39
  246.131580.792   258.6 1573.67   265.2 1572.08   291.4  1570.9  340.421569.979
   396.1 1569.25     406 1567.73   415.8 1568.18  434.471566.576   435.4 1566.52
     442 1566.19   451.8 1566.57   464.9 1567.19   471.4 1570.42   474.7  1570.7
   484.5 1569.47     514 1569.22   641.7 1572.95   710.4 1573.92   759.5 1575.43
#Mann= 8 ,-1 , 0
       0     .06       0  145.52     .12       0  209.27    .016       0
  246.13     .06       0  340.42     .12       0  434.47     .06       0
   435.4    .045       0   451.8     .06       0
Bank Sta=435.4,451.8
XS Rating Curve= 0 ,0
Exp/Cntr=0.3,0.1

Type RM Length L Ch R = 1 ,3040.2  ,377.9,374.9,370.4
XS GIS Cut Line= 3
     2022662.843      291146.289     2023232.762      291272.352
     2023452.773      291280.837
#Sta/Elev= 30
       0 1601.59    42.6 1595.29   108.2 1588.72  160.851587.321   191.11587.448
   213.2 1587.85   216.4 1587.26   219.7 1584.33  221.351583.775     223 1583.22
   242.7 1583.11   249.2 1580.14  254.431576.033   262.3 1568.62   268.9 1566.54
   285.3  1566.2   327.9 1567.16     341 1564.72   360.7 1563.68   367.3 1563.36
   380.4 1563.57   393.5 1563.99   409.9 1565.81   432.8 1566.01   439.4 1567.08
     446 1569.28  451.74 1569.78   680.8 1570.72     765 1572.74   803.9 1574.38
#Mann= 8 ,-1 , 0
       0     .06       0  160.85     .08       0   191.1     .12       0
  221.35    .016       0  254.43     .12       0   360.7    .045       0
   380.4     .12       0  451.74     .06       0
Bank Sta=360.7,380.4
XS Rating Curve= 0 ,0
Exp/Cntr=0.3,0.1

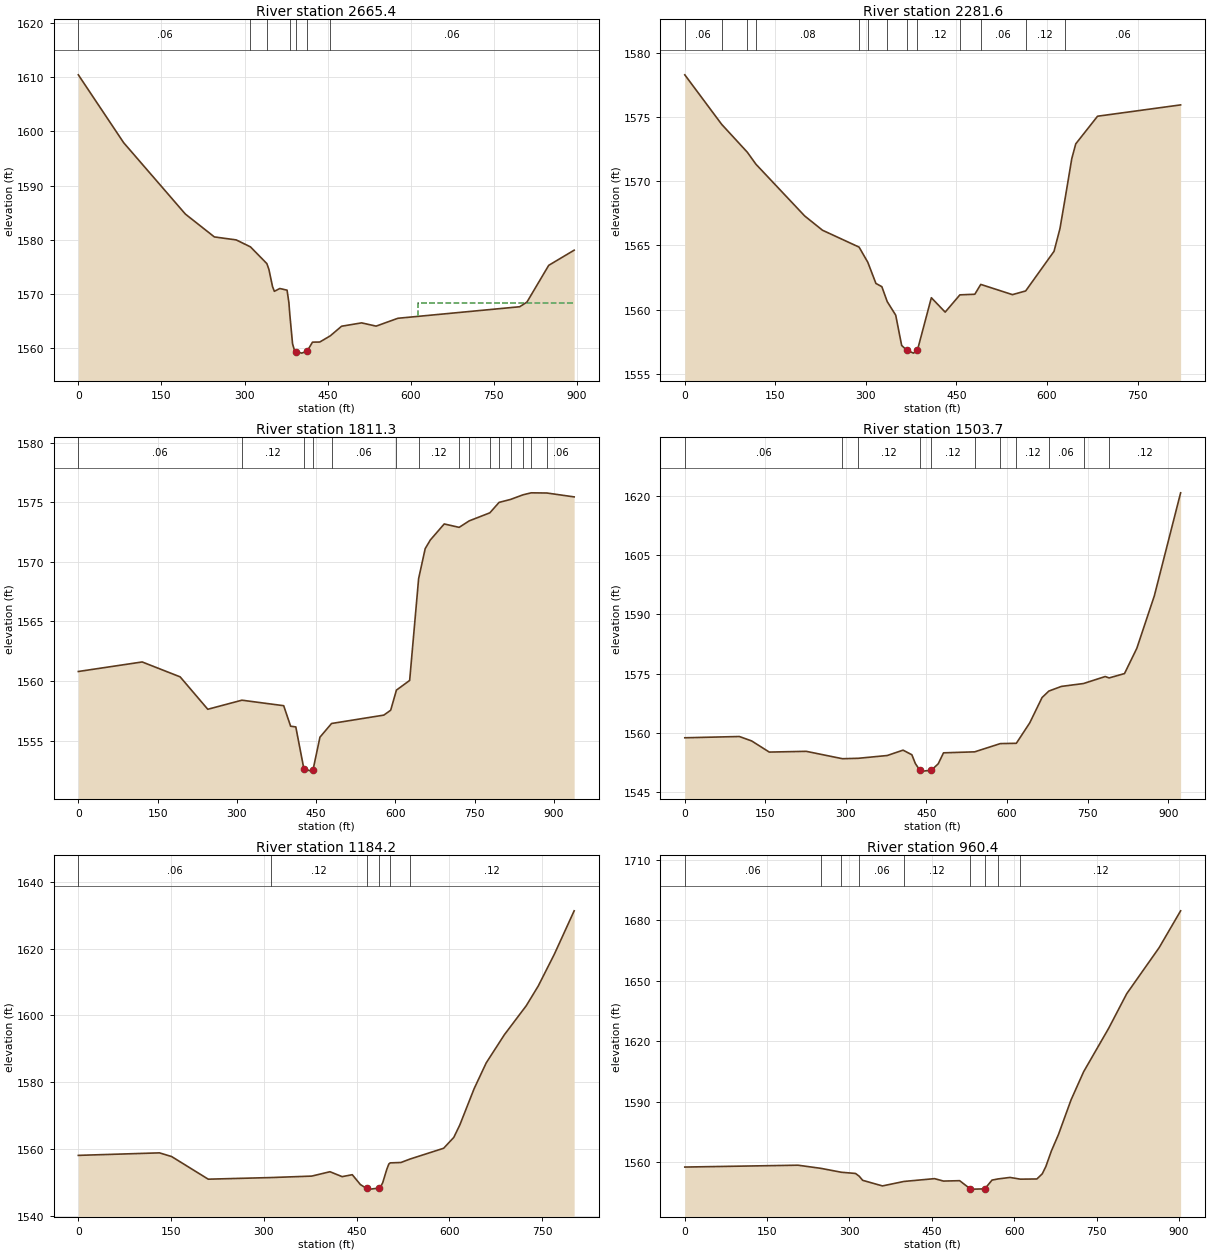
Type RM Length L Ch R = 1 ,2665.4  ,382.2,383.8,383.8
XS GIS Cut Line= 3
     2022612.929      291402.365      2022784.37      291578.146
     2023433.242      291602.018
#Sta/Elev= 30
       0 1610.45    81.8 1597.91   193.2 1584.72   245.5  1580.5   284.9 1579.95
  310.641578.663   340.21575.573   343.9 1574.51   350.5 1571.31   353.8 1570.45
   363.6 1570.97   376.7 1570.66     380 1568.36  381.65 1566.18   386.6 1560.76
   389.8 1559.62   393.1 1559.33     403 1559.03   412.8 1559.38   422.6 1561.06
   435.7 1561.08  454.561562.215   475.1    1564   511.2 1564.62   537.4 1564.02
   576.8 1565.47   796.5  1567.6   809.6 1568.46   848.9 1575.25   894.8 1578.05
#Mann= 7 ,-1 , 0
       0     .06       0  310.64     .12       0   340.2    .016       0
  381.65     .12       0   393.1    .045       0   412.8     .12       0
  454.56     .06       0
#XS Ineff= 2 , 0
                          612.22         1568.37
Permanent Ineff=
       F       F
Bank Sta=393.1,412.8
XS Rating Curve= 0 ,0
Exp/Cntr=0.3,0.1

Type RM Length L Ch R = 1 ,2281.6  ,470.7,470.3,469.3
XS GIS Cut Line= 3
     2022608.589      291847.244     2022731.925       291942.73
     2023396.349      291977.452
#Sta/Elev= 30
       0 1578.27   61.081574.419  103.581572.249   117.81571.318   198.6 1567.29
   228.1 1566.18  288.721564.866  303.211563.681   316.6 1562.04   326.4 1561.79
  335.281560.631   349.4 1559.57   359.2 1557.22   367.6 1556.85   378.8 1556.62
   385.4 1556.86   408.4 1560.93   431.3 1559.81  455.661561.153   480.4  1561.2
  490.231561.966   542.7 1561.17  564.621561.457   611.6 1564.54   621.4  1566.3
  629.741568.585     641 1571.75   647.6  1572.9   683.7 1575.05   821.3 1575.93
#Mann= 13 ,-1 , 0
       0     .06       0   61.08     .08       0  103.58     .06       0
   117.8     .08       0  288.72     .12       0  303.21    .016       0
  335.28     .12       0   367.6    .045       0   385.4     .12       0
  455.66    .016       0  490.23     .06       0  564.62     .12       0
  629.74     .06       0
Bank Sta=367.6,385.4
XS Rating Curve= 0 ,0
Exp/Cntr=0.3,0.1

Type RM Length L Ch R = 1 ,1811.3  ,306.5,307.6,307.8
XS GIS Cut Line= 3
     2022454.509      292402.799      2023113.87       292415.82
     2023324.373      292233.528
#Sta/Elev= 30
       0  1560.8   120.8  1561.6   192.6 1560.35   244.9 1557.63  309.431558.392
   388.5 1557.93   401.6 1556.21   411.4 1556.15   426.7 1552.63   440.8 1552.44
     444 1552.55   457.1 1555.29  479.051556.437   577.9 1557.14   590.9 1557.55
  601.791559.238   626.8 1560.05  643.761568.593   656.2 1571.11     666 1571.84
   692.2 1573.18  720.421572.894  739.471573.439  778.541574.114     796 1574.99
  817.621575.236  841.121575.623  856.691575.792  886.241575.777     938 1575.45
#Mann= 15 ,-1 , 0
       0     .06       0  309.43     .12       0   426.7    .045       0
     444     .12       0  479.05     .06       0  601.79    .016       0
  643.76     .12       0  720.42     .08       0  739.47     .12       0
  778.54     .06       0     796     .12       0  817.62    .016       0
  841.12     .08       0  856.69    .016       0  886.24     .06       0
Bank Sta=426.7,444
XS Rating Curve= 0 ,0
Exp/Cntr=0.3,0.1

Type RM Length L Ch R = 1 ,1503.7  ,312.9,319.5,325.1
XS GIS Cut Line= 3
     2022467.403      292697.095     2023148.592       292721.81
     2023330.884       292880.23
#Sta/Elev= 30
       0 1558.78   101.6  1559.1   124.5 1557.98   157.3 1555.16   226.1 1555.35
  293.58 1553.48  323.141553.589   376.9 1554.29   406.4 1555.65   422.8 1554.48
   429.3 1552.26   437.4 1550.61   442.4 1550.34   458.8 1550.54   471.9  1552.2
   481.7 1554.97  539.781555.222  587.551557.308  617.291557.383   642.3 1562.56
   665.2 1568.96  677.831570.599   701.2 1571.78  742.39 1572.51   782.8 1574.28
  790.081573.925   818.7 1575.03   841.6 1581.41   874.2 1594.68   923.2 1620.77
#Mann= 11 ,-1 , 0
       0     .06       0  293.58     .08       0  323.14     .12       0
   437.4    .045       0   458.8     .12       0  539.78     .06       0
  587.55    .016       0  617.29     .12       0  677.83     .06       0
  742.39     .08       0  790.08     .12       0
Bank Sta=437.4,458.8
XS Rating Curve= 0 ,0
Exp/Cntr=0.3,0.1

Type RM Length L Ch R = 1 ,1184.2  ,215.5,223.8,231.9
XS GIS Cut Line= 3
     2022487.625      292875.723     2023127.816      293081.886
     2023223.303      293168.692
#Sta/Elev= 30
       0 1558.08   131.2 1558.83   150.9 1557.72     210 1550.95  312.181551.439
   377.3 1551.87   406.8 1553.18   426.5 1551.71   442.9 1552.29     456 1549.34
   465.9 1548.18   472.4 1547.97   485.6 1548.28   488.8 1548.69   492.1  1549.9
   498.7 1553.91     502  1555.5   504.2 1555.83   521.6 1555.95  536.341556.985
   590.6 1560.21     607 1563.46   616.8 1567.21   639.8 1578.02   659.4 1585.77
   688.7 1594.19   724.2 1602.91   743.5 1608.79   769.4 1618.26   801.6 1631.32
#Mann= 6 ,-1 , 0
       0     .06       0  312.18     .12       0   465.9    .045       0
   485.6     .08       0   504.2    .016       0  536.34     .12       0
Bank Sta=465.9,485.6
XS Rating Curve= 0 ,0
Exp/Cntr=0.3,0.1

Type RM Length L Ch R = 1 ,960.4   ,329.7,341.4,352.9
XS GIS Cut Line= 2
     2022419.425       292886.74      2023124.72      293450.976
#Sta/Elev= 30
       0 1557.52   206.2 1558.44  248.031556.874  285.181554.939   310.9 1554.35
  317.671552.989     324 1550.94     360 1548.16  399.341550.385   454.9 1551.77
   471.2 1550.57   500.7 1550.76   519.9 1546.72   526.9 1546.57   546.5  1546.7
   559.6 1551.05  570.281551.612   592.3 1552.37  611.251551.517   641.4 1551.61
   651.2 1554.18   657.8 1557.85   667.6 1565.39   680.7 1573.69   703.6 1590.85
   726.5  1604.8   772.3 1626.45     805 1643.52     864 1666.35   903.2 1684.65
#Mann= 9 ,-1 , 0
       0     .06       0  248.03     .08       0  285.18     .12       0
  317.67     .06       0  399.34     .12       0   519.9    .045       0
   546.5     .12       0  570.28    .016       0  611.25     .12       0
Bank Sta=519.9,546.5
XS Rating Curve= 0 ,0
Exp/Cntr=0.3,0.1

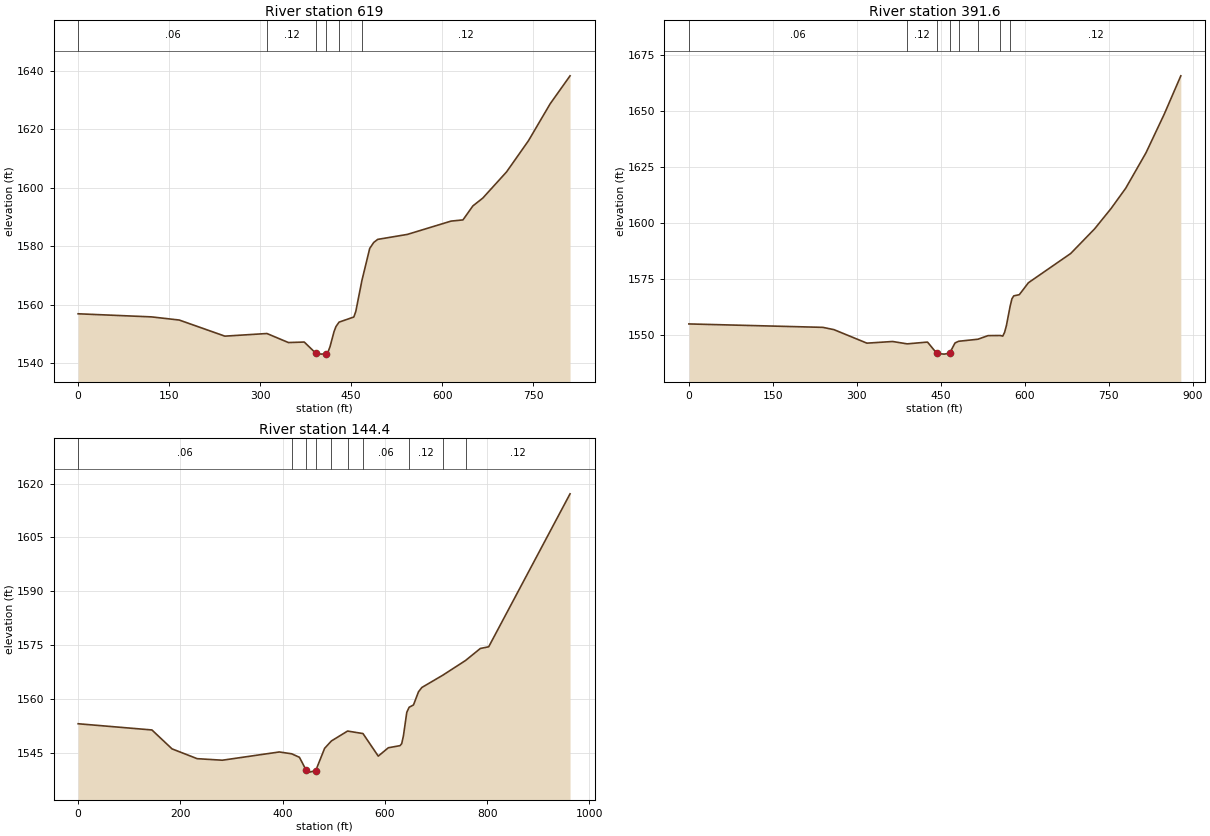
Type RM Length L Ch R = 1 ,619     ,221.8,227.4,233
XS GIS Cut Line= 2
     2022416.011      293023.292        2022722.      293774.161
#Sta/Elev= 30
       0 1556.88     121 1555.82   166.7 1554.74   241.9 1549.23  311.181550.132
   346.6 1547.04   372.7 1547.21   392.1 1543.32   402.1 1543.08   408.7 1543.27
     412 1543.88   415.2 1545.65   421.8 1550.79     425 1552.53  430.051554.022
   454.4 1555.78   457.7 1557.73  467.731568.271   480.6 1579.25   487.2 1581.28
   493.7 1582.33   542.7 1584.04   614.7 1588.59   634.3    1589   650.6 1593.78
     667 1596.47   706.2 1605.44   742.2 1616.07   778.1 1628.75   810.8 1638.29
#Mann= 6 ,-1 , 0
       0     .06       0  311.18     .12       0   392.1    .045       0
   408.7     .12       0  430.05    .016       0  467.73     .12       0
Bank Sta=392.1,408.7
XS Rating Curve= 0 ,0
Exp/Cntr=0.3,0.1

Type RM Length L Ch R = 1 ,391.6   ,239.3,247.2,254.3
XS GIS Cut Line= 2
     2022280.536      292986.567     2022402.064      293856.792
#Sta/Elev= 30
       0 1554.98   239.3 1553.45     259 1552.44     318  1546.4   363.9 1547.14
  389.861546.083   426.2 1546.88     443 1541.79   455.7  1541.5   465.6 1541.87
   475.4 1546.49  481.791547.238   516.3 1548.15   534.4 1549.76  556.271549.819
   560.6 1549.54   563.9 1551.21   567.2 1554.28  573.791562.846     577 1566.19
   580.3 1567.51   590.2 1568.04   606.5 1573.38     682 1586.43   724.6  1597.4
   754.1  1606.5   780.3 1615.58   816.4 1631.34   849.2  1648.7   878.7 1665.75
#Mann= 8 ,-1 , 0
       0     .06       0  389.86     .12       0     443    .045       0
   465.6     .12       0  481.79     .06       0   516.3    .016       0
  556.27     .08       0  573.79     .12       0
Bank Sta=443,465.6
XS Rating Curve= 0 ,0
Exp/Cntr=0.3,0.1

Type RM Length L Ch R = 1 ,144.4   ,121.2,144.4,166.3
XS GIS Cut Line= 3
      2022187.22      292990.907     2022041.821      293730.924
     2022128.627      293919.726
#Sta/Elev= 30
       0 1553.06   144.3 1551.33   183.6 1546.06   232.8 1543.33     282  1542.9
   393.5  1545.2  417.55 1544.69   432.8 1543.71   445.9 1540.13   452.5 1539.58
   464.6 1539.98     482 1546.21  495.281548.264  526.921551.024  557.031550.328
   586.9 1544.04   606.6 1546.37   629.6 1546.96   632.8 1547.53   636.1 1549.65
   642.7 1556.24  647.331557.656   655.8  1558.3   665.6 1561.96   672.2 1563.17
  713.261566.601  757.571570.683   786.6 1574.04   802.9 1574.51     962 1617.13
#Mann= 10 ,-1 , 0
       0     .06       0  417.55     .12       0   445.9    .045       0
   464.6     .12       0  495.28     .06       0  526.92    .016       0
  557.03     .06       0  647.33     .12       0  713.26     .06       0
  757.57     .12       0
Bank Sta=445.9,464.6
XS Rating Curve= 0 ,0
Exp/Cntr=0.3,0.1

Chan Stop Cuts=-1
Use User Specified Reach Order=0
Composite Channel Slope=5